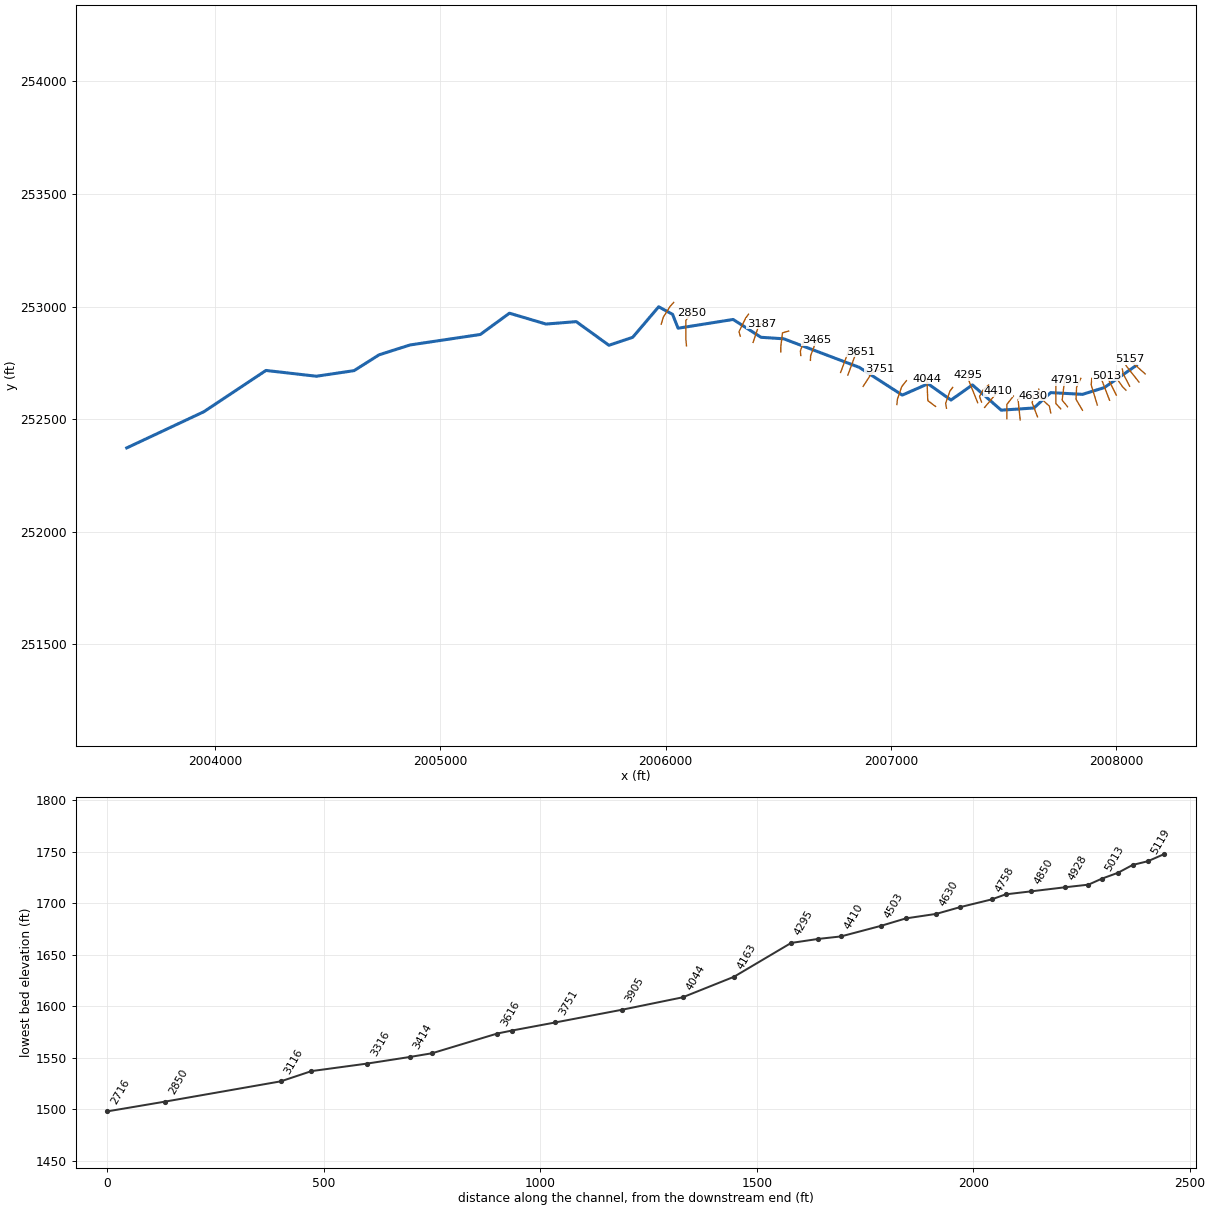
--- TUGCK.prj (project) ---

Proj Title=TUGCK
Current Plan=p01
Default Exp/Contr=0,0
English Units
Geom File=g01
Flow File=f01
Plan File=p01
BEGIN DESCRIPTION:
Stream Name: Tug Creek
Flood Zone: Approximate
Summers County, West Virginia
HEC-RAS Version: 5.0.7
Hydrology Method:
regression
Model Notes:
END DESCRIPTION:
DSS Export Rating Curves= 0
DSS Export Rating Curve Sorted= 0
DSS Export Volume Flow Curves= 0
DXF OffsetX= 0
DXF OffsetY= 0
DXF ScaleX= 0
DXF ScaleY= 0

--- TUGCK.p01 (plan) ---

Plan Title=Floodplain
Program Version=5.07
Short Identifier=Floodplain
Geom File=g01
Flow File=f01
Subcritical Flow
K Sum by GR= 0
Std Step Tol= 0.01
Critical Tol= 0.01
Num of Std Step Trials= 20
Max Error Tol= 0.3
Flow Tol Ratio= 0.001
Split Flow NTrial= 30
Split Flow Tol= 0.02
Split Flow Ratio= 0.02
Log Output Level= 0
Friction Slope Method= 1
Unsteady Friction Slope Method= 2
Unsteady Bridges Friction Slope Method= 1
Parabolic Critical Depth
Global Vel Dist= 0 , 0 , 0
Global Log Level= 0
CheckData=True
Encroach Param=-1 ,0,0, 0
Mapping Interval=1HOUR
Computation Time Step Use Courant=        0
Computation Time Step Use Time Series=    0
Computation Time Step Count To Double=0
Computation Time Step Max Doubling=0
Computation Time Step Max Halving=0
Computation Time Step Residence Courant=0
Run HTab= 0
Run UNet= 0
Run Sediment= 0
Run PostProcess= 0
Run WQNet= 0
Run RASMapper= 0
UNET Theta= 0
UNET Theta Warmup= 0
UNET ZTol= 0
UNET ZSATol= 0
UNET MxIter= 0
UNET Max Iter WO Improvement= 0
UNET MaxInSteps= 0
UNET DtIC= 0
UNET DtMin= 0
UNET MaxCRTS= 0
UNET WFStab= 0
UNET SFStab= 0
UNET WFX= 1
UNET SFX= 1
UNET 1D Methodology=Finite Difference
UNET DSS MLevel= 1
UNET Pardiso=0
UNET DZMax Abort= 0
UNET Use Existing IB Tables= 0
UNET Froude Reduction=False
UNET Froude Limit= 0
UNET Froude Power= 0
UNET D1 Cores= 0
UNET D2 Coriolis=0
UNET D2 Cores= 0
UNET D2 Theta= 1
UNET D2 Theta Warmup= 1
UNET D2 Z Tol= 0.01
UNET D2 Volume Tol= 0.01
UNET D2 Max Iterations= 20
UNET D2 Equation= 0
UNET D2 RampUpFraction=0.1
UNET D2 TimeSlices= 1
UNET D2 BCVolumeCheck=0
UNET D1D2 MaxIter= 0
UNET D1D2 ZTol=0.01
UNET D1D2 QTol=0.1
UNET D1D2 MinQTol=1
Write IC File= 0
Write IC File at Fixed DateTime=0
Write IC File at Sim End=0
Echo Input=False
Echo Parameters=False
Echo Output=False
Write Detailed= 0
HDF Write Warmup=0
HDF Write Time Slices=0
HDF Flush=0
HDF Face Node Velocities=0
HDF Compression= 1
HDF Chunk Size= 1
HDF Spatial Parts= 1
HDF Use Max Rows=0
HDF Fixed Rows= 1
Calibration Method= 0
Calibration Iterations= 20
Calibration Max Change=0.05
Calibration Tolerance=0.2
Calibration Maximum=1.5
Calibration Minimum=0.5
Calibration Optimization Method= 1
WQ AD Non Conservative
WQ ULTIMATE=-1
WQ Max Comp Step=1HOUR
WQ Output Interval=15MIN
WQ Output Selected Increments= 0
WQ Output face flow=0
WQ Output face velocity=0
WQ Output face area=0
WQ Output face dispersion=0
WQ Output cell volume=0
WQ Output cell surface area=0
WQ Output cell continuity=0
WQ Output cumulative cell continuity=0
WQ Output face conc=0
WQ Output face dconc_dx=0
WQ Output face courant=0
WQ Output face peclet=0
WQ Output face adv mass=0
WQ Output face disp mass=0
WQ Output cell mass=0
WQ Output cell source sink temp=0
WQ Output nsm pathways=0
WQ Output nsm derived pathways=0
WQ Output MaxMinRange=-1
WQ Daily Max Min Mean=-1
WQ Daily Range=0
WQ Daily Time=0
WQ Create Restart=0
WQ Fixed Restart=0
WQ System Summary=0
WQ Write To DSS=0
WQ Use Fixed Temperature=0
Sorting and Armoring Iterations= 10
XS Update Threshold= 0.02
Bed Roughness Predictor= 0
Hydraulics Update Threshold= 0.02
Energy Slope Method= 1
Volume Change Method= 1
Sediment Retention Method= 0
XS Weighting Method= 0
Number of US Weighted Cross Sections= 1
Number of DS Weighted Cross Sections= 1
Upstream XS Weight=0
Main XS Weight=1
Downstream XS Weight=0
Number of DS XS's Weighted with US Boundary= 1
Upstream Boundary Weight= 1
Weight of XSs Associated with US Boundary= 0
Number of US XS's Weighted with DS Boundary= 1
Downstream Boundary Weight= 0.5
Weight of XSs Associated with DS Boundary= 0.5
Percentile Method= 0
Sediment Output Level= 3
Mass or Volume Output= 0
Output Increment Type= 1
Profile and TS Output Increment= 1
XS Output Flag= 0
XS Output Increment= 10
Write Gradation File= 0
Read Gradation Hotstart= 0
Write HDF5 File= 1
Write Binary Output= 1
Write DSS Sediment File= 0
SV Curve= 0
Specific Gage Flag= 0

--- TUGCK.f01 (steady flow) ---

Flow Title=Flows
Program Version=5.07
Number of Profiles= 6
Profile Names=01pct,10pct,04pct,02pct,0_2pct,01plus
River Rch & RM=TUGCK,Main            ,5157
     474     249     332     401     665     702
River Rch & RM=TUGCK,Main            ,4758
     584     309     410     494     815     863
River Rch & RM=TUGCK,Main            ,3905
     662     352     467     561     922     979
River Rch & RM=TUGCK,Main            ,3187
     738     394     522     627    1027    1092
Boundary for River Rch & Prof#=TUGCK,Main            , 1
Up Type= 0
Dn Type= 3
Dn Slope=0.060912
Boundary for River Rch & Prof#=TUGCK,Main            , 2
Up Type= 0
Dn Type= 3
Dn Slope=0.060912
Boundary for River Rch & Prof#=TUGCK,Main            , 3
Up Type= 0
Dn Type= 3
Dn Slope=0.060912
Boundary for River Rch & Prof#=TUGCK,Main            , 4
Up Type= 0
Dn Type= 3
Dn Slope=0.060912
Boundary for River Rch & Prof#=TUGCK,Main            , 5
Up Type= 0
Dn Type= 3
Dn Slope=0.060912
Boundary for River Rch & Prof#=TUGCK,Main            , 6
Up Type= 0
Dn Type= 3
Dn Slope=0.060912
DSS Import GetInterval= 0
DSS Import GetPeak= 0
DSS Import FillOption= 0

--- TUGCK.g01 (geometry) ---

Geom Title=Geometry
Program Version=5.07

River Reach=TUGCK           ,Main
Reach XY= 30
     2008089.495      252738.701     2007947.134       252640.09
     2007850.297      252610.231      2007708.94      252617.867
     2007634.845      252549.641     2007489.359      252539.919
2007361.63076696 252652.11191981     2007266.616      252584.884
2007164.57339242252657.111407463      2007050.47      252606.759
     2006859.526      252729.991     2006524.428      252856.759
     2006423.346      252863.473     2006299.735      252942.639
     2006055.291       252903.75     2006030.852      252965.439
      2005969.18      252998.889     2005853.902      252863.473
     2005748.346      252828.056     2005603.248      252932.974
     2005469.072      252922.263      2005306.68      252970.417
     2005177.513      252875.973     2004865.707      252829.445
     2004728.207      252785.695      2004617.31      252715.439
     2004449.735      252690.556     2004226.124      252716.251
     2003950.123        252532.8     2003608.029      252372.262

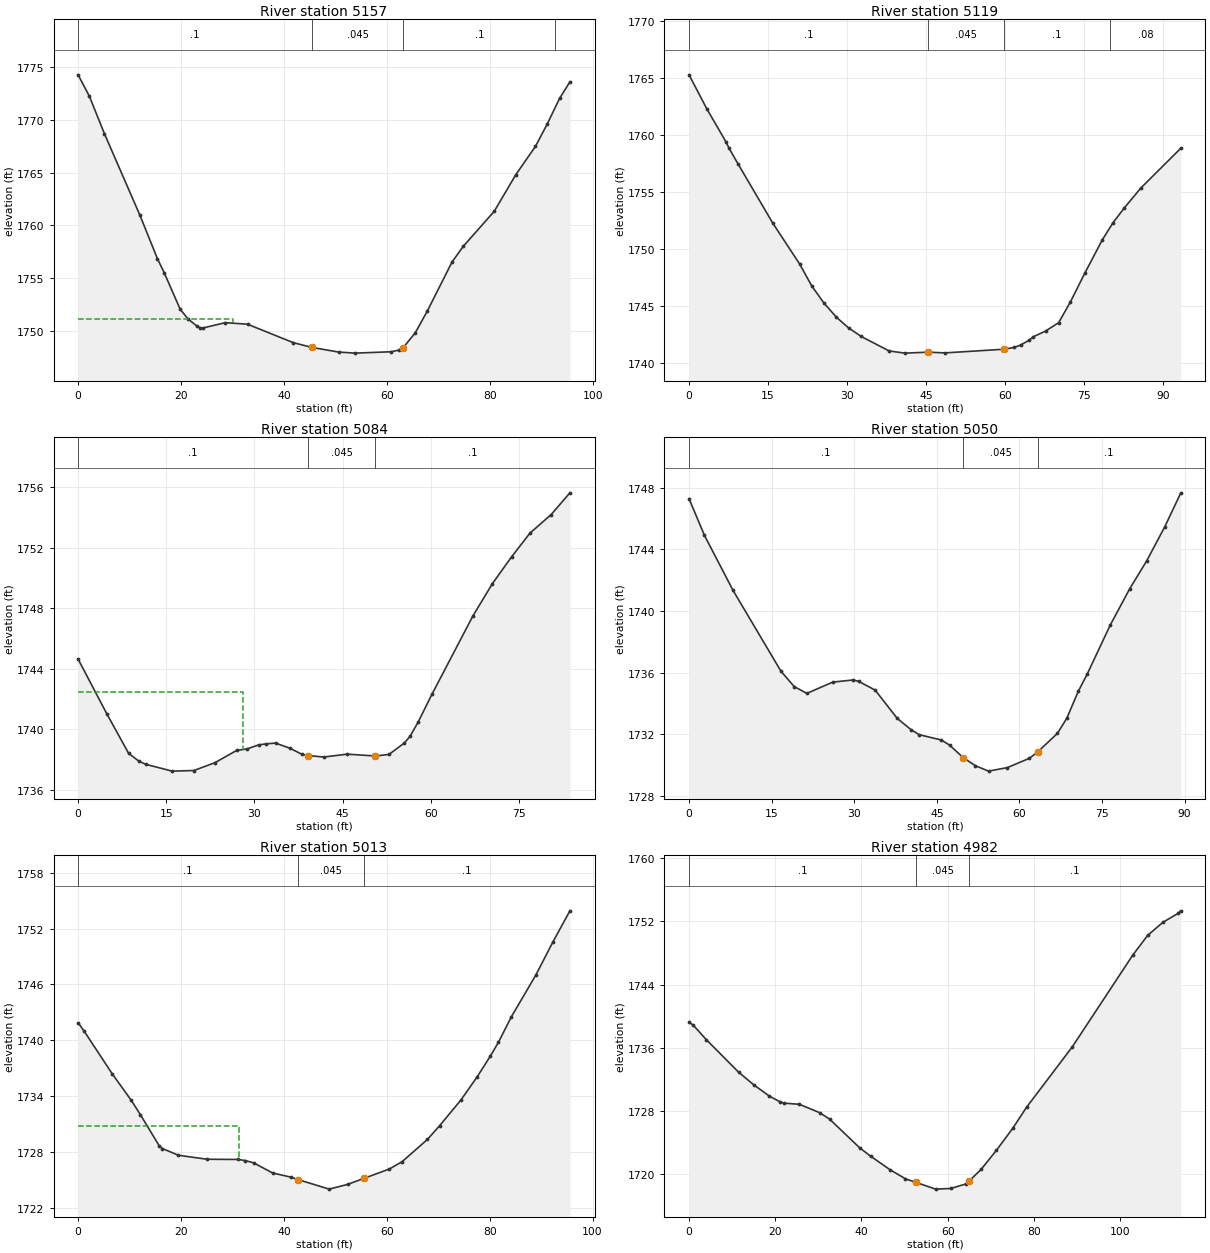
Type RM Length L Ch R = 1 ,5157    ,72.9,38.1,72.9
XS GIS Cut Line= 3
2008128.49631124252700.9619996512008074.28140333252749.389033516
2008059.85352464252767.088329664
#Sta/Elev= 30
       0 1774.27     2.2 1772.22     5.1  1768.7      12 1760.96    15.4 1756.84
    16.7 1755.53    19.8 1752.07    21.3 1751.15      23 1750.48    23.6  1750.3
    24.2 1750.27    28.6 1750.78    32.9 1750.63    41.8 1748.88    45.41748.433
    50.6 1747.99    53.8 1747.89    60.8 1748.02    62.4 1748.19    63.1 1748.39
    65.5 1749.84    67.8 1751.87    72.6 1756.52    74.8 1758.02    80.8 1761.33
      85 1764.81    88.8 1767.48    91.1 1769.61    93.5 1772.04    95.5  1773.6
#Mann= 4 ,-1 , 0
       0      .1       0    45.4    .045       0    63.1      .1       0
   92.69     .08       0
#XS Ineff= 2 , 0
           29.99 1751.08
Permanent Ineff=
       F       F
Bank Sta=45.4,63.1
XS Rating Curve= 0 ,0
Exp/Cntr(USF)=0,0
Exp/Cntr=0.3,0.1

Type RM Length L Ch R = 1 ,5119    ,38,35.3,33.8
XS GIS Cut Line= 2
2008101.09138083252664.3598588362008043.42391086252737.804278129
#Sta/Elev= 30
       0 1765.26     3.4 1762.26       7  1759.4     7.6 1758.83     9.3 1757.46
    15.9 1752.27      21 1748.69    23.3 1746.77    25.6 1745.28      28 1744.02
    30.3 1743.09    32.7 1742.34      38 1741.07      41 1740.88    45.41740.964
    48.6  1740.9    59.81741.221    61.8 1741.38      63  1741.6    64.6 1742.01
    65.4 1742.32    67.7 1742.81    70.2 1743.55    72.4 1745.34    75.2 1747.92
    78.5 1750.81    80.5 1752.29    82.7 1753.62    85.8 1755.34    93.4 1758.83
#Mann= 4 ,-1 , 0
       0      .1       0    45.4    .045       0    59.8      .1       0
      80     .08       0
Bank Sta=45.4,59.8
XS Rating Curve= 0 ,0
Exp/Cntr(USF)=0,0
Exp/Cntr=0.3,0.1

Type RM Length L Ch R = 1 ,5084    ,32.2,33.9,35.4
XS GIS Cut Line= 3
 2008059.4187629252646.2993383742008030.50844405 252702.54304959
2008027.00416297252722.692665758
#Sta/Elev= 30
       0 1744.63     4.9 1741.01     8.6 1738.41    10.4 1737.88    11.6 1737.68
      16 1737.24    19.7 1737.28    23.3  1737.8      27 1738.61    28.7  1738.7
    30.7 1738.97      32 1739.04    33.6 1739.09      36 1738.76    38.1 1738.35
    39.1 1738.27    41.8 1738.17    45.8 1738.36    50.6 1738.24    52.9 1738.34
    55.5 1739.09    56.5 1739.54    57.9  1740.5    60.2  1742.3    67.2 1747.49
    70.5 1749.61    73.8  1751.4    76.9 1752.95    80.5 1754.17    83.7 1755.61
#Mann= 3 ,-1 , 0
       0      .1       0    39.1    .045       0    50.6      .1       0
#XS Ineff= 2 , 0
              28 1742.45
Permanent Ineff=
       F       F
Bank Sta=39.1,50.6
XS Rating Curve= 0 ,0
Exp/Cntr(USF)=0,0
Exp/Cntr=0.3,0.1

Type RM Length L Ch R = 1 ,5050    ,38.5,36.8,35
XS GIS Cut Line= 4
2008043.13983863252628.5803109552008027.97381556252643.746334027
2007999.94964249252684.2989609352007998.30116172252702.761945544
#Sta/Elev= 30
       0 1747.28     2.8  1744.9       8 1741.33    16.7 1736.09    19.1  1735.1
    21.4 1734.66    26.1 1735.39    29.8 1735.53    30.8 1735.44    33.8 1734.87
    37.8 1733.04    40.3 1732.31    41.8 1731.98    45.8 1731.64    47.3 1731.31
    49.8 1730.49      52 1729.97    54.4 1729.62    57.8 1729.85    61.8 1730.45
    63.3 1730.86    66.9 1732.07    68.6 1733.05    70.7 1734.81    72.3 1735.91
    76.5  1739.1      80 1741.43    83.1 1743.25    86.4 1745.47    89.3 1747.66
#Mann= 3 ,-1 , 0
       0      .1       0    49.8    .045       0    63.3      .1       0
Bank Sta=49.8,63.3
XS Rating Curve= 0 ,0
Exp/Cntr(USF)=0,0
Exp/Cntr=0.3,0.1

Type RM Length L Ch R = 1 ,5013    ,32.5,31.3,30.2
XS GIS Cut Line= 2
2008000.17330839 252606.964405242007957.73875502252692.649561082
#Sta/Elev= 30
       0 1741.89     1.2 1740.96     6.6 1736.42    10.3 1733.57    12.1 1732.01
    15.8 1728.62    16.4 1728.36    19.5 1727.64    25.1 1727.21    31.1 1727.19
    32.5 1727.07    34.1 1726.83    37.8 1725.74    41.4 1725.28    42.81725.016
    48.8    1724    52.4 1724.51    55.61725.167    60.5 1726.16      63 1726.96
    67.9 1729.34    70.3 1730.84    74.4 1733.57    77.6  1736.1    80.1 1738.27
    81.7 1739.78    84.2 1742.51      89 1747.04    92.3 1750.58    95.6 1753.92
#Mann= 3 ,-1 , 0
       0      .1       0    42.8    .045       0    55.6      .1       0
#XS Ineff= 2 , 0
           31.32 1730.83
Permanent Ineff=
       F       F
Bank Sta=42.8,55.6
XS Rating Curve= 0 ,0
Exp/Cntr(USF)=0,0
Exp/Cntr=0.3,0.1

Type RM Length L Ch R = 1 ,4982    ,55,54.2,53.4
XS GIS Cut Line= 2
 2007970.3699125252584.121158857 2007929.4343567252690.663252746
#Sta/Elev= 30
       0 1739.25       1 1738.84       4 1737.03    11.5 1732.91      15 1731.32
    18.6  1729.9    21.1 1729.16    22.1 1728.99    25.6 1728.85    30.3 1727.79
    32.6 1726.98    39.6 1723.34    42.1  1722.3    46.7 1720.55    50.2 1719.43
    52.71718.966    57.2 1718.12    60.7  1718.2    64.2 1718.77      65 1719.15
    67.8 1720.64    71.3 1723.02    75.1 1725.81    78.3 1728.47    88.9  1736.1
   102.9 1747.68   106.4 1750.21   109.9 1751.85   113.5 1753.01   114.1 1753.32
#Mann= 3 ,-1 , 0
       0      .1       0    52.7    .045       0      65      .1       0
Bank Sta=52.7,65
XS Rating Curve= 0 ,0
Exp/Cntr(USF)=0,0
Exp/Cntr=0.3,0.1

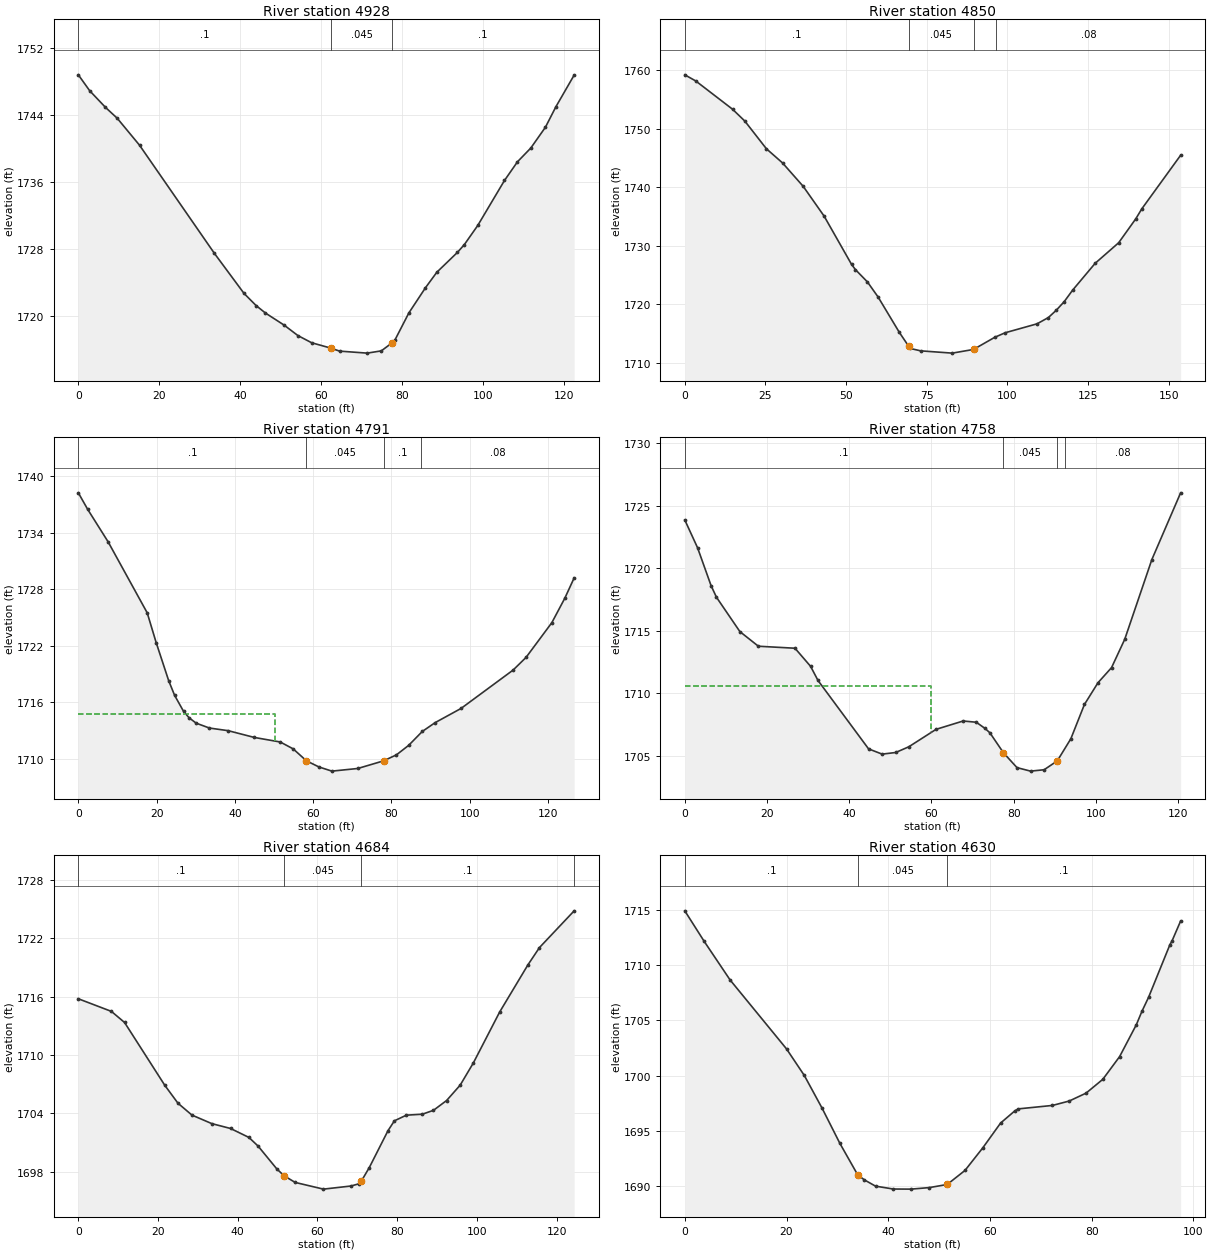
Type RM Length L Ch R = 1 ,4928    ,82.2,77.8,71.8
XS GIS Cut Line= 3
 2007916.0341914252562.6871921812007888.90631174252652.260379716
2007891.46554567252680.923799727
#Sta/Elev= 30
       0 1748.84     2.8 1746.94     6.7 1744.95     9.6 1743.65    15.1 1740.43
    33.6 1727.49    40.9 1722.71    43.9 1721.25    46.2 1720.36    50.8 1718.92
    54.2 1717.67    57.6 1716.81    62.31716.172    64.5 1715.81    71.3 1715.57
    74.8 1715.84    77.51716.818    78.2 1717.18    81.6 1720.38    85.7 1723.39
    88.5 1725.24    93.6 1727.62    95.3 1728.55    98.6 1730.83   105.2 1736.21
   108.4 1738.44   111.7 1740.09   115.3 1742.57   117.9 1745.03   122.4 1748.81
#Mann= 3 ,-1 , 0
       0      .1       0    62.3    .045       0    77.5      .1       0
Bank Sta=62.3,77.5
XS Rating Curve= 0 ,0
Exp/Cntr(USF)=0,0
Exp/Cntr=0.3,0.1

Type RM Length L Ch R = 1 ,4850    ,60.1,59.2,57.9
XS GIS Cut Line= 4
2007850.17332816252539.4732212952007821.53031527252588.216594122
2007824.04286026 252641.985056932007842.63569319252681.180758791
#Sta/Elev= 30
       0 1759.21     3.4 1758.16    14.8 1753.33    18.6 1751.31    25.3 1746.57
    30.3 1744.15    36.7 1740.15    43.2 1735.05    51.7  1726.8    52.9 1725.91
    56.6 1723.82    59.9 1721.25    66.5 1715.19    69.4 1712.81    69.8 1712.45
    73.1 1712.03    82.9 1711.64    89.5 1712.27    96.1 1714.35    99.3 1715.12
   109.2 1716.65   112.7 1717.72   115.1 1718.94   117.6 1720.43   120.2 1722.39
   127.2 1726.99   134.5 1730.51   139.8  1734.6   141.7 1736.33   153.7 1745.46
#Mann= 4 ,-1 , 0
       0      .1       0    69.4    .045       0    89.5      .1       0
   96.54     .08       0
Bank Sta=69.4,89.5
XS Rating Curve= 0 ,0
Exp/Cntr(USF)=0,0
Exp/Cntr=0.3,0.1

Type RM Length L Ch R = 1 ,4791    ,31.6,32.5,33.8
XS GIS Cut Line= 3
2007783.86138241252555.2026312482007760.02921352252584.363732315
2007770.83510376252672.735190877
#Sta/Elev= 30
       0 1738.23     2.4 1736.47     7.6 1733.04    17.6  1725.5    19.9 1722.33
    23.1 1718.29    24.6 1716.75    26.9 1715.04    28.3 1714.37    30.1  1713.8
    33.5 1713.28    38.3    1713      45 1712.28    51.6  1711.8    54.9 1711.07
    58.3  1709.8    61.5 1709.15    64.8 1708.71    71.4 1708.99      78  1709.8
    81.3 1710.44    84.4 1711.44    87.9 1712.92    91.2 1713.86    97.8 1715.36
   111.1 1719.43   114.4 1720.77     121 1724.46   124.3 1727.04   126.7 1729.21
#Mann= 4 ,-1 , 0
       0      .1       0    58.3    .045       0      78      .1       0
   87.66     .08       0
#XS Ineff= 2 , 0
           50.31  1714.8
Permanent Ineff=
       F       F
Bank Sta=58.3,78
XS Rating Curve= 0 ,0
Exp/Cntr(USF)=0,0
Exp/Cntr=0.3,0.1

Type RM Length L Ch R = 1 ,4758    ,63.8,73.7,82.7
XS GIS Cut Line= 3
2007753.88311538252545.6432513312007731.90965401252569.473624929
2007731.90965401252657.676955781
#Sta/Elev= 30
       0 1723.86     3.1 1721.64     6.4  1718.6     7.7 1717.68    13.4 1714.93
    17.9 1713.76    26.8  1713.6    30.6 1712.15    32.4 1711.02    44.7 1705.55
      48 1705.13    51.3 1705.26    54.5 1705.72    61.1 1707.11    67.7 1707.78
    70.9 1707.68      73 1707.19    74.2 1706.84    77.5 1705.24    80.8 1704.05
    84.1 1703.77    87.4 1703.88    90.6 1704.59    93.9 1706.36    97.2  1709.1
   100.5 1710.84   103.8 1712.05     107 1714.31   113.6 1720.69   120.6 1726.03
#Mann= 4 ,-1 , 0
       0      .1       0    77.5    .045       0    90.6      .1       0
   92.41     .08       0
#XS Ineff= 2 , 0
           59.88 1710.55
Permanent Ineff=
       F       F
Bank Sta=77.5,90.6
XS Rating Curve= 0 ,0
Exp/Cntr(USF)=0,0
Exp/Cntr=0.3,0.1

Type RM Length L Ch R = 1 ,4684    ,61.6,54.1,49.3
XS GIS Cut Line= 4
2007709.45251632252527.6982653222007703.32470597252557.780243423
2007662.37979133252595.3827160492007656.25198098252632.985188675
#Sta/Elev= 30
       0 1715.78     8.3 1714.48    11.6 1713.34    21.7 1706.87      25 1705.03
    28.5 1703.81    33.5 1702.93    38.2 1702.43    42.8 1701.51    45.1 1700.62
    49.8 1698.27    51.6 1697.57    54.4 1696.88    61.5 1696.19    68.4 1696.51
    70.4 1696.74      71 1697.01      73 1698.41    77.7 1702.21    79.3 1703.22
    82.3  1703.8    86.3  1703.9    89.1  1704.3    92.4 1705.31    95.8 1706.89
    99.1 1709.17   105.7 1714.41   112.8 1719.27   115.7 1721.05   124.4 1724.83
#Mann= 4 ,-1 , 0
       0      .1       0    51.6    .045       0      71      .1       0
  124.39     .08       0
Bank Sta=51.6,71
XS Rating Curve= 0 ,0
Exp/Cntr(USF)=0,0
Exp/Cntr=0.3,0.1

Type RM Length L Ch R = 1 ,4630    ,72.4,70.4,65.2
XS GIS Cut Line= 3
2007650.47171954252510.5490879212007627.06329263252572.531964822
2007631.34934263252603.523403272
#Sta/Elev= 30
       0 1714.89     3.8 1712.14     8.9 1708.65      20 1702.42    23.5 1700.02
      27 1697.06    30.5 1693.88      34 1691.04    35.3 1690.59    37.5 1690.02
      41 1689.76    44.5 1689.75    48.1 1689.89    51.6 1690.17    55.1 1691.44
    58.6 1693.48    62.1 1695.72    64.9 1696.82    65.6    1697    72.3 1697.31
    75.6 1697.71    78.9 1698.42    82.2 1699.67    85.5 1701.72    88.8 1704.61
    89.9 1705.82    91.2 1707.08    95.4 1711.84    95.8 1712.16    97.5 1713.97
#Mann= 3 ,-1 , 0
       0      .1       0      34    .045       0    51.6      .1       0
Bank Sta=34,51.6
XS Rating Curve= 0 ,0
Exp/Cntr(USF)=0,0
Exp/Cntr=0.3,0.1

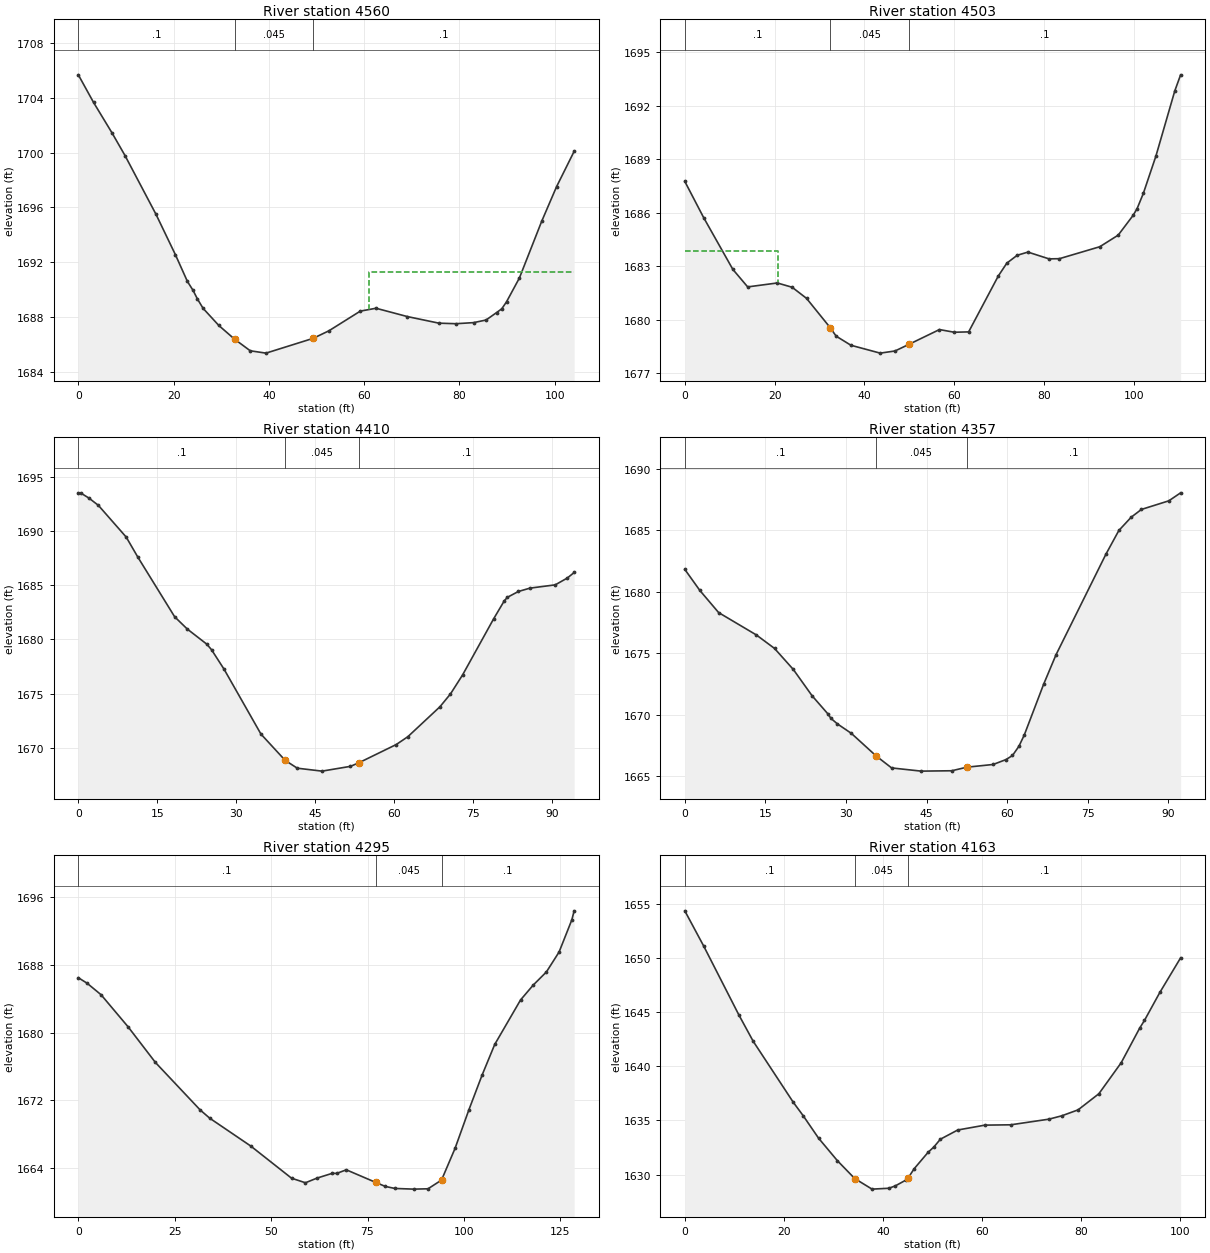
Type RM Length L Ch R = 1 ,4560    ,57.2,57.3,54.6
XS GIS Cut Line= 3
2007573.72419523 252496.600179882007564.44385985252586.002182873
2007571.99762121252598.088201045
#Sta/Elev= 30
       0 1705.69     3.2 1703.67     7.1 1701.43     9.8 1699.79    16.3  1695.5
    20.4 1692.53    22.9 1690.59    24.1 1689.93      25 1689.31    26.2 1688.62
    29.5 1687.37    32.8 1686.37    36.1 1685.52    39.4 1685.35    49.3 1686.43
    52.6 1686.98    59.2 1688.42    62.5 1688.63    69.1 1688.02    75.7 1687.54
    79.3  1687.5      83 1687.58    85.6 1687.77    87.8 1688.31    88.9 1688.59
    89.9  1689.1    92.6 1690.84    97.3    1695   100.4 1697.51   104.1  1700.1
#Mann= 3 ,-1 , 0
       0      .1       0    32.8    .045       0    49.3      .1       0
#XS Ineff= 2 , 0
                           61.01         1691.31
Permanent Ineff=
       F       F
Bank Sta=32.8,49.3
XS Rating Curve= 0 ,0
Exp/Cntr(USF)=0,0
Exp/Cntr=0.3,0.1

Type RM Length L Ch R = 1 ,4503    ,102.7,92.4,86.3
XS GIS Cut Line= 3
2007514.50370696252502.1217245362007514.63690421252565.608345594
2007543.65016573252602.534314811
#Sta/Elev= 30
       0 1687.75     4.2 1685.72    10.7 1682.82      14 1681.84    20.6 1682.06
    23.9 1681.82    27.1  1681.2    32.41679.549    33.7 1679.08      37 1678.57
    43.5 1678.13    46.8 1678.25    49.91678.621    56.7 1679.45      60  1679.3
    63.2 1679.32    69.8 1682.45    71.7 1683.17      74 1683.61    76.4 1683.79
    81.1 1683.41    83.4 1683.42    92.4 1684.09    96.5 1684.74    99.8 1685.84
   100.7 1686.22   102.1 1687.08   104.9 1689.17   109.1 1692.82   110.4 1693.72
#Mann= 3 ,-1 , 0
       0      .1       0    32.4    .045       0    49.9      .1       0
#XS Ineff= 2 , 0
           20.73 1683.87
Permanent Ineff=
       F       F
Bank Sta=32.4,49.9
XS Rating Curve= 0 ,0
Exp/Cntr(USF)=0,0
Exp/Cntr=0.3,0.1

Type RM Length L Ch R = 1 ,4410    ,49.6,52.7,55.4
XS GIS Cut Line= 2
2007415.73816245252551.8143997022007475.85042149252624.352097769
#Sta/Elev= 30
       0  1693.5      .5 1693.47       2 1693.02     3.8 1692.35     9.1 1689.42
    11.3 1687.58    18.3 1682.08    20.7 1680.95    24.4 1679.56    25.3 1679.05
    27.7 1677.24    34.7 1671.27    39.3 1668.85    41.6 1668.13    46.3 1667.86
    51.7  1668.3    53.3 1668.63    60.4 1670.31    62.6 1671.03    68.7 1673.79
    70.7 1674.97      73 1676.72    78.9 1681.89    80.9 1683.53    81.5 1683.87
    83.6 1684.41    85.8 1684.72    90.6 1685.02    92.9 1685.65    94.2 1686.16
#Mann= 3 ,-1 , 0
       0      .1       0    39.3    .045       0    53.3      .1       0
Bank Sta=39.3,53.3
XS Rating Curve= 0 ,0
Exp/Cntr(USF)=0,0
Exp/Cntr=0.3,0.1

Type RM Length L Ch R = 1 ,4357    ,50.4,62.4,73.8
XS GIS Cut Line= 4
2007402.21051579252575.8289263592007393.30871964252600.885834042
2007410.12322348252631.2178801852007433.53165039252651.659041716
#Sta/Elev= 29
       0 1681.81     2.8  1680.1     6.3  1678.3    13.3 1676.49    16.7 1675.39
    20.2 1673.68    23.7 1671.54    26.6 1670.09    27.2 1669.71    28.4 1669.26
      31 1668.49    35.6 1666.66    38.5 1665.68      44 1665.42    49.7 1665.45
    52.5 1665.74    57.4 1665.96    59.8 1666.36      61 1666.69    62.2 1667.44
    63.2 1668.36    66.8 1672.48    69.1 1674.87    78.4 1683.05    80.8 1684.97
    83.1 1686.05      85 1686.68    90.1 1687.38    92.3 1688.03
#Mann= 3 ,-1 , 0
       0      .1       0    35.6    .045       0    52.5      .1       0
Bank Sta=35.6,52.5
XS Rating Curve= 0 ,0
Exp/Cntr(USF)=0,0
Exp/Cntr=0.3,0.1

Type RM Length L Ch R = 1 ,4295    ,138.4,132.2,124.1
XS GIS Cut Line= 3
 2007384.9694339252573.0425914122007346.79540369252668.477666937
2007342.12517659 252693.85933596
#Sta/Elev= 30
       0 1686.47     2.3 1685.81     5.9 1684.46    12.9 1680.68      20 1676.47
    31.6 1670.87    34.1 1669.89    44.7 1666.62    55.3 1662.82    58.9 1662.28
    61.9 1662.83    65.9  1663.4      67 1663.38    69.5 1663.81    77.1 1662.33
    79.6 1661.85    82.1 1661.61      87 1661.53    90.7 1661.57    94.2  1662.6
    97.7 1666.33   101.3 1670.89   104.7 1674.96     108  1678.6   114.7 1683.85
     118 1685.61   121.4 1687.15   124.7 1689.51     128  1693.3   128.6 1694.36
#Mann= 3 ,-1 , 0
       0      .1       0    77.1    .045       0    94.2      .1       0
Bank Sta=77.1,94.2
XS Rating Curve= 0 ,0
Exp/Cntr(USF)=0,0
Exp/Cntr=0.3,0.1

Type RM Length L Ch R = 1 ,4163    ,108.1,118.4,118.4
XS GIS Cut Line= 4
2007246.59393123  252548.46414562007242.89671856   252570.048034
2007261.53839848252624.1432601192007274.14367152252640.911276801
#Sta/Elev= 30
       0 1654.35     3.8 1651.11    10.9 1644.75    13.8 1642.31    21.9 1636.67
    23.9 1635.43      27 1633.36    30.8 1631.28    34.3 1629.63    37.8 1628.65
    41.2 1628.73    42.5 1628.95    44.7  1629.5    45.1 1629.69    46.3 1630.53
    49.1 1632.04    50.3 1632.55    51.6 1633.26    55.1 1634.11    60.6 1634.56
    65.8 1634.59    73.5 1635.11    76.1 1635.42    79.4 1635.97    83.6 1637.46
    88.1 1640.32    91.8 1643.49    92.8 1644.23    95.9 1646.81   100.1 1650.01
#Mann= 3 ,-1 , 0
       0      .1       0    34.3    .045       0    45.1      .1       0
Bank Sta=34.3,45.1
XS Rating Curve= 0 ,0
Exp/Cntr(USF)=0,0
Exp/Cntr=0.3,0.1

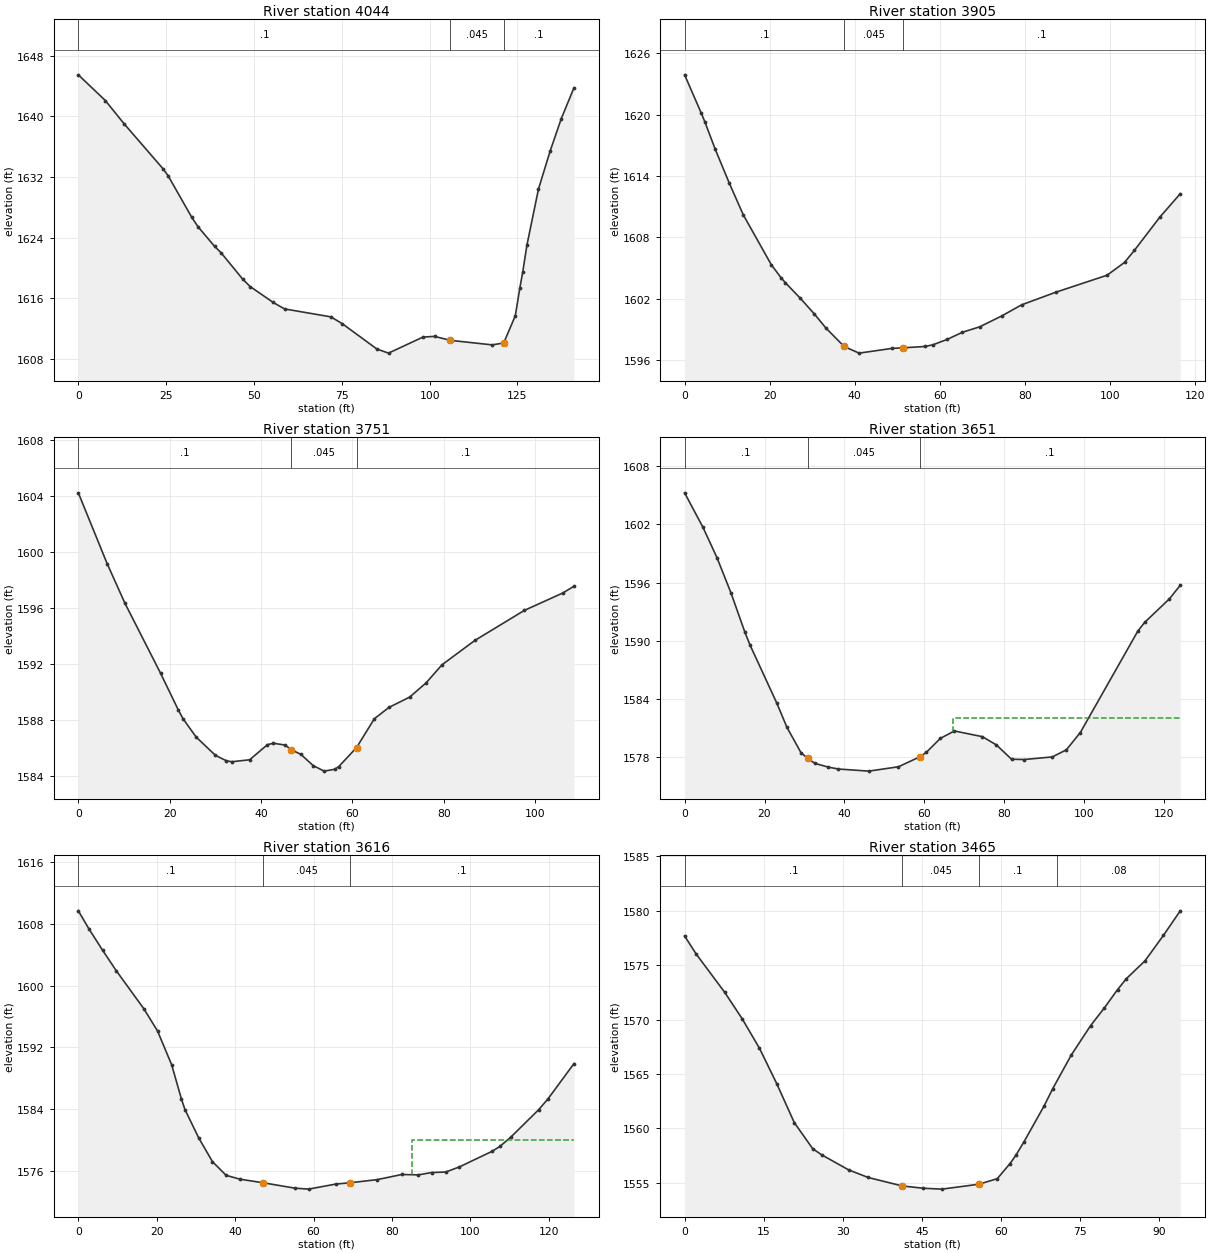
Type RM Length L Ch R = 1 ,4044    ,144.9,139.9,136.3
XS GIS Cut Line= 3
2007197.92227996252556.5034009852007163.65789002252582.369656136
2007159.62678532252680.459870472
#Sta/Elev= 30
       0  1645.5     7.7  1642.1      13 1639.05    24.1  1633.1    25.6 1632.14
    32.3 1626.67    34.1 1625.42    38.8 1622.84    40.6 1622.02    46.8 1618.51
    48.9 1617.54    55.5 1615.43    58.7 1614.58    71.9 1613.53    75.2 1612.61
      85 1609.28    88.3 1608.74    98.1 1610.86   101.4 1610.95   105.9 1610.43
   117.8 1609.83   121.1 1610.08   124.4 1613.68   125.7 1617.38   126.5 1619.41
   127.7 1622.99     131 1630.42   134.3 1635.41   137.5 1639.73   141.1 1643.79
#Mann= 3 ,-1 , 0
       0      .1       0   105.9    .045       0   121.1      .1       0
Bank Sta=105.9,121.1
XS Rating Curve= 0 ,0
Exp/Cntr(USF)=0,0
Exp/Cntr=0.3,0.1

Type RM Length L Ch R = 1 ,3905    ,157.7,154,152
XS GIS Cut Line= 4
2007026.38533476252564.753853823 2007028.8550886252588.696874685
2007047.75412247252643.8642208872007068.61831905252670.823961453
#Sta/Elev= 29
       0 1623.91     3.9 1620.18     4.8 1619.27     7.2 1616.63    10.5 1613.32
    13.8 1610.21    20.4 1605.32    22.7 1604.05    23.7 1603.57    27.1  1602.1
    30.5 1600.52    33.2 1599.15    37.5 1597.34      41 1596.69    48.7 1597.15
    51.3 1597.21    56.5 1597.34    58.4 1597.51    61.7 1598.03    65.3 1598.73
    69.4 1599.27    74.6 1600.34    79.2 1601.41    87.2 1602.64    99.3 1604.31
   103.4 1605.56   105.7 1606.73   111.7 1609.99   116.5 1612.28
#Mann= 3 ,-1 , 0
       0      .1       0    37.5    .045       0    51.3      .1       0
Bank Sta=37.5,51.3
XS Rating Curve= 0 ,0
Exp/Cntr(USF)=0,0
Exp/Cntr=0.3,0.1

Type RM Length L Ch R = 1 ,3751    ,92.5,100,101.5
XS GIS Cut Line= 3
2006876.67484675252645.3948147952006915.57899289252705.729210927
2006949.20800057252720.565537845
#Sta/Elev= 30
       0 1604.23     6.3 1599.18    10.2 1596.35      18 1591.35    21.9 1588.72
    22.9 1588.11    25.8 1586.79      30 1585.49    32.4  1585.1    33.6 1585.03
    37.5 1585.17    41.4 1586.25    42.7 1586.35    45.3 1586.22    46.6 1585.89
    48.7 1585.56    51.4 1584.76    53.8 1584.36    56.1 1584.49      57 1584.68
    60.9 1586.04    64.8  1588.1      68 1588.91    72.5 1589.64    76.1 1590.65
    79.6 1591.95    86.8 1593.69    97.6 1595.83     106 1597.07   108.5 1597.56
#Mann= 3 ,-1 , 0
       0      .1       0    46.6    .045       0    60.9      .1       0
Bank Sta=46.6,60.9
XS Rating Curve= 0 ,0
Exp/Cntr(USF)=0,0
Exp/Cntr=0.3,0.1

Type RM Length L Ch R = 1 ,3651    ,38,34.1,35.6
XS GIS Cut Line= 3
2006808.82084338252695.5709800362006843.43812992252789.372659702
2006865.21351985252799.422839666
#Sta/Elev= 30
       0 1605.27     4.6  1601.7     8.1 1598.57    11.6 1594.93    15.1 1590.85
    16.4 1589.51    23.1 1583.51    25.6 1581.04    29.1 1578.43    30.8 1577.82
    32.6 1577.31    35.9 1576.93    38.4 1576.73    46.1 1576.51    53.5 1576.96
    58.9    1578    60.5 1578.46      64  1579.9    67.5 1580.66    74.5 1580.07
      78 1579.22    81.8 1577.74      85 1577.71      92 1577.98    95.5 1578.71
      99  1580.5   113.4 1590.99   115.1 1591.88   121.3 1594.32     124 1595.72
#Mann= 3 ,-1 , 0
       0      .1       0    30.8    .045       0    58.9      .1       0
#XS Ineff= 2 , 0
                            67.2         1581.95
Permanent Ineff=
       F       F
Bank Sta=30.8,58.9
XS Rating Curve= 0 ,0
Exp/Cntr(USF)=0,0
Exp/Cntr=0.3,0.1

Type RM Length L Ch R = 1 ,3616    ,150.9,150.9,151.1
XS GIS Cut Line= 3
2006776.63481312252707.1650376772006813.70024382252807.063961344
2006830.52364946252817.570388675
#Sta/Elev= 30
       0 1609.71     2.7 1607.37     6.2 1604.59     9.7 1601.92    16.7 1597.01
    20.2 1594.12    23.8 1589.74    26.3 1585.28    27.2 1583.92    30.7 1580.25
    34.2 1577.17    37.7 1575.39    41.2 1574.89    47.2 1574.42    55.2 1573.73
    58.7  1573.6    65.7 1574.26    69.2 1574.42    76.2 1574.83    82.5  1575.5
    86.7 1575.45    90.1 1575.75    93.7 1575.82    97.2 1576.49   105.5  1578.5
   107.5 1579.14   110.3 1580.35   117.4 1583.91   119.8 1585.33   126.4 1589.89
#Mann= 3 ,-1 , 0
       0      .1       0    47.2    .045       0    69.2      .1       0
#XS Ineff= 2 , 0
                              85            1580
Permanent Ineff=
       F       F
Bank Sta=47.2,69.2
XS Rating Curve= 0 ,0
Exp/Cntr(USF)=0,0
Exp/Cntr=0.3,0.1

Type RM Length L Ch R = 1 ,3465    ,50.6,51.2,51.2
XS GIS Cut Line= 3
2006642.64462452252761.1355628692006643.69044397252781.712964692
2006669.29596605252850.465822413
#Sta/Elev= 29
       0 1577.68     2.2 1576.02     7.6 1572.51    10.9 1570.09    14.2 1567.37
    17.5 1564.09    20.8 1560.54    24.3 1558.14      26 1557.58    31.1  1556.2
    34.8  1555.5    41.3 1554.72    45.3 1554.51    48.8 1554.43    55.8 1554.88
    59.3 1555.39    61.7 1556.77    62.8 1557.52    64.3 1558.72    68.2 1562.09
    69.8 1563.64    73.3 1566.72      77 1569.45    79.6 1571.07    82.1 1572.75
    83.8 1573.77    87.3 1575.39    90.8 1577.73      94 1579.99
#Mann= 4 ,-1 , 0
       0      .1       0    41.3    .045       0    55.8      .1       0
    70.6     .08       0
Bank Sta=41.3,55.8
XS Rating Curve= 0 ,0
Exp/Cntr(USF)=0,0
Exp/Cntr=0.3,0.1

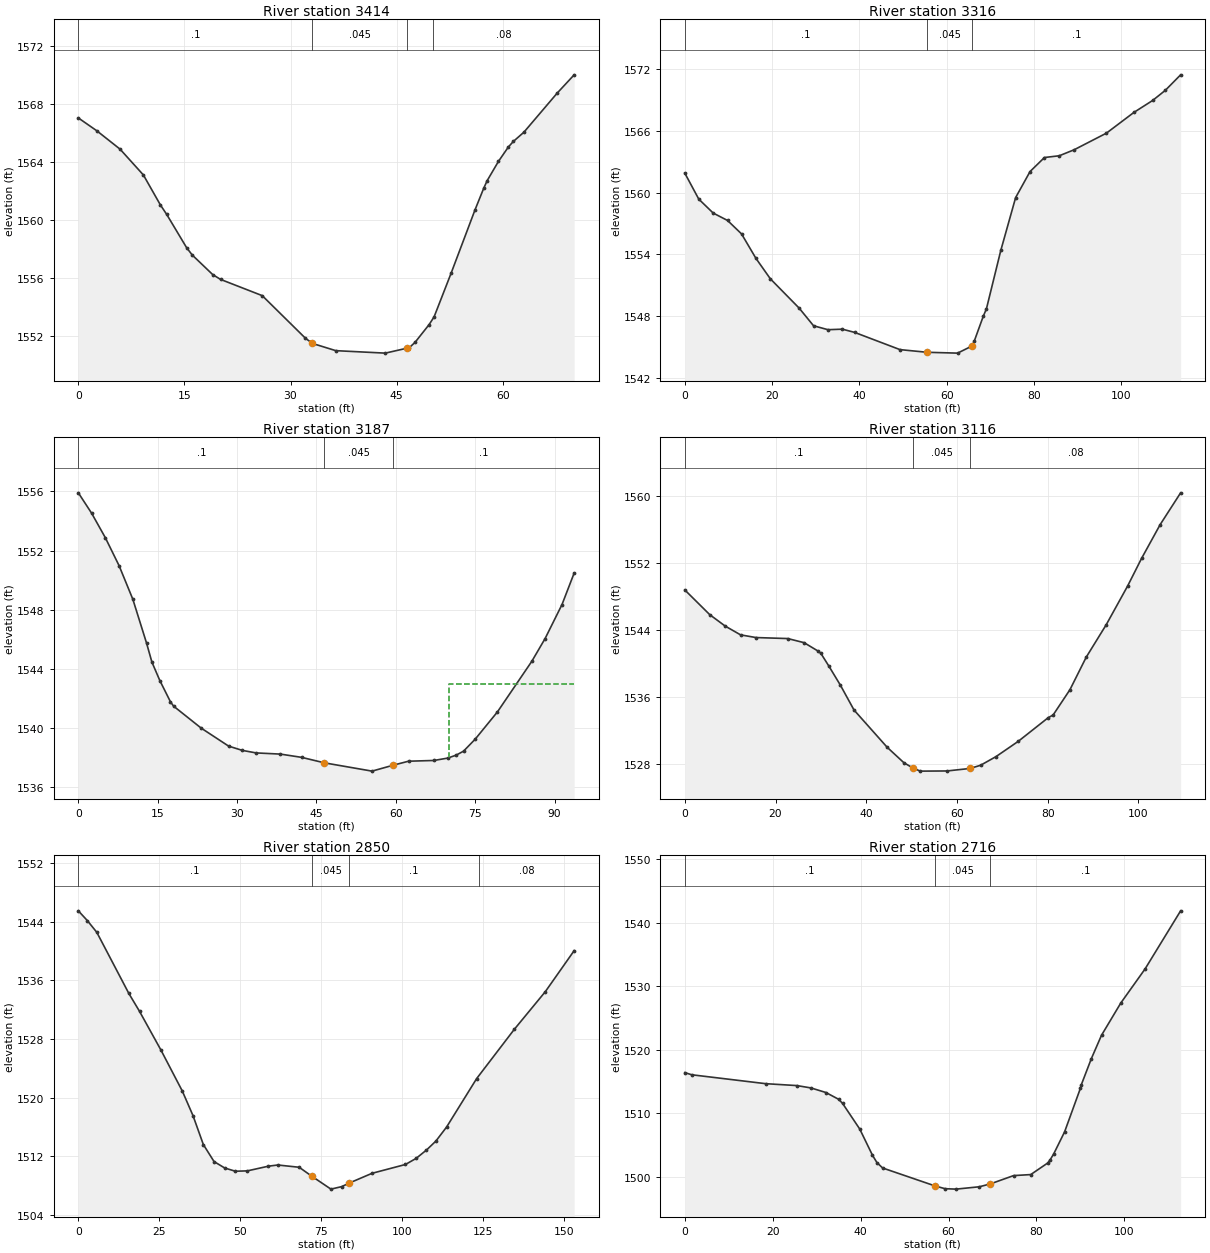
Type RM Length L Ch R = 1 ,3414    ,95.9,98.1,100.1
XS GIS Cut Line= 3
2006599.91376535252782.6144777952006597.96400751252802.669129861
2006614.67621757252849.741854852
#Sta/Elev= 30
       0 1567.03     2.6 1566.15     5.9 1564.88     9.2  1563.1    11.6 1561.04
    12.5 1560.38    15.3  1558.1    16.1 1557.59      19 1556.24    20.1 1555.91
      26 1554.79    32.1 1551.86    33.11551.498    36.4    1551    43.4 1550.83
    46.51551.174    46.8 1551.21    47.6 1551.57    49.6  1552.8    50.3 1553.33
    52.7 1556.33    56.1 1560.72    57.3 1562.17    57.8 1562.71    59.4 1564.04
    60.8 1565.03    61.5 1565.41      63 1566.05    67.7 1568.74    70.1    1570
#Mann= 4 ,-1 , 0
       0      .1       0    33.1    .045       0    46.5      .1       0
   50.15     .08       0
Bank Sta=33.1,46.5
XS Rating Curve= 0 ,0
Exp/Cntr(USF)=0,0
Exp/Cntr=0.3,0.1

Type RM Length L Ch R = 1 ,3316    ,126.9,129.2,126.4
XS GIS Cut Line= 4
2006511.02565716252798.380094351 2006511.1588544252820.715360285
 2006518.6248238252883.1057416322006545.89663025252891.156921706
#Sta/Elev= 30
       0 1561.88     3.2 1559.36     6.5 1558.01     9.8 1557.29      13 1555.99
    16.3 1553.62    19.6 1551.64    26.2  1548.8    29.5 1547.09    32.8 1546.71
    36.1 1546.76    38.9 1546.45    49.3 1544.78    55.51544.522    62.5 1544.44
    65.8 1545.13    66.3 1545.58    68.4 1548.03    69.1 1548.72    72.4 1554.39
    75.8 1559.51    79.1 1562.03    82.4 1563.39    85.8 1563.56    89.2 1564.14
    96.6 1565.75   102.9 1567.76   107.2 1568.92   110.1  1569.9   113.6  1571.4
#Mann= 3 ,-1 , 0
       0      .1       0    55.5    .045       0    65.8      .1       0
Bank Sta=55.5,65.8
XS Rating Curve= 0 ,0
Exp/Cntr(USF)=0,0
Exp/Cntr=0.3,0.1

Type RM Length L Ch R = 1 ,3187    ,73.9,70.6,68.9
XS GIS Cut Line= 3
2006388.18856533252840.8623493962006413.45834688 252915.92811377
2006425.30921161252924.351272166
#Sta/Elev= 30
       0  1555.9     2.5 1554.53     5.1 1552.87     7.7 1550.98    10.3 1548.71
    12.9 1545.74    13.9 1544.47    15.4 1543.22    17.4 1541.79      18 1541.49
    23.2 1540.01    28.4 1538.79      31  1538.5    33.6 1538.33    38.2 1538.25
    42.2 1538.03    46.5 1537.66    55.5  1537.1    59.5  1537.5    62.4 1537.77
    67.2 1537.82    69.8 1537.98    71.4 1538.18    72.8 1538.45      75 1539.26
    79.2  1541.1    85.7 1544.52    88.2 1546.05    91.4 1548.35    93.7 1550.48
#Mann= 3 ,-1 , 0
       0      .1       0    46.5    .045       0    59.5      .1       0
#XS Ineff= 2 , 0
                              70            1543
Permanent Ineff=
       F       F
Bank Sta=46.5,59.5
XS Rating Curve= 0 ,0
Exp/Cntr(USF)=0,0
Exp/Cntr=0.3,0.1

Type RM Length L Ch R = 1 ,3116    ,261.6,266.6,271.6
XS GIS Cut Line= 4
2006331.31296113252868.4833529332006325.63351096252888.235773744
2006355.51051288252948.9695420962006367.98254832252965.963742087
#Sta/Elev= 30
       0  1548.8     5.5 1545.85     8.9 1544.49    12.3 1543.44    15.7 1543.12
    22.7    1543    26.3 1542.51    29.4  1541.5      30 1541.23    31.8 1539.68
    34.3 1537.44    37.3 1534.48    44.6 1530.04    48.3 1528.19    50.3 1527.56
    51.9 1527.19    57.8 1527.21    62.9 1527.51    65.2 1527.89    68.6 1528.92
    73.5 1530.74    80.1 1533.56    81.2 1533.89    84.9  1536.9    88.5 1540.79
    92.9 1544.65    97.6 1549.25   100.7 1552.57   104.8  1556.6   109.3 1560.38
#Mann= 3 ,-1 , 0
       0      .1       0    50.3    .045       0    62.9     .08       0
Bank Sta=50.3,62.9
XS Rating Curve= 0 ,0
Exp/Cntr(USF)=0,0
Exp/Cntr=0.3,0.1

Type RM Length L Ch R = 1 ,2850    ,136.5,133.9,125
XS GIS Cut Line= 4
2006092.59718276252825.3981447552006089.84992297252855.792584698
2006089.83510402252938.9193621312006115.13807504252969.195556789
#Sta/Elev= 30
       0  1545.5     2.8 1544.16     5.7 1542.57    15.6 1534.23    18.9 1531.79
    25.5 1526.52    32.1 1520.93    35.4 1517.58    38.6 1513.63    41.9 1511.31
    45.2 1510.43    48.5 1509.99    52.2 1510.04    58.7 1510.68    61.6 1510.84
    68.2 1510.53      721509.339      78 1507.55    81.3 1507.89    83.71508.387
    90.7 1509.71     101 1510.91   104.3 1511.74   107.5 1512.88   110.4  1514.1
   113.7 1516.01     123 1522.63   134.6 1529.33   144.2 1534.48   153.1 1540.07
#Mann= 4 ,-1 , 0
       0      .1       0      72    .045       0    83.7      .1       0
  123.65     .08       0
Bank Sta=72,83.7
XS Rating Curve= 0 ,0
Exp/Cntr(USF)=0,0
Exp/Cntr=0.3,0.1

Type RM Length L Ch R = 1 ,2716    ,145.2,166.8,174.7
XS GIS Cut Line= 4
2005980.47059909252921.7317433272005989.75516024252953.024153102
2006020.35982474253001.1663219872006035.83409331253018.359953731
#Sta/Elev= 30
       0 1516.38     1.6 1516.04    18.4 1514.64    25.5 1514.34    28.7 1513.97
    32.1 1513.25      35 1512.18    35.9 1511.53    39.8  1507.5    42.7 1503.37
    43.7 1502.23      45 1501.37    56.9 1498.55    59.2 1498.11    61.7 1498.04
      67 1498.41    69.5 1498.86    74.8 1500.17    78.7 1500.33    82.6 1502.17
    83.1 1502.64    83.9 1503.55    86.4 1507.05      90 1513.91    90.2 1514.46
    92.5  1518.6    94.8 1522.26    99.2 1527.35   104.7 1532.69   112.8 1541.85
#Mann= 3 ,-1 , 0
       0      .1       0    56.9    .045       0    69.5      .1       0
Bank Sta=56.9,69.5
XS Rating Curve= 0 ,0
Exp/Cntr(USF)=0,0
Exp/Cntr=0.3,0.1