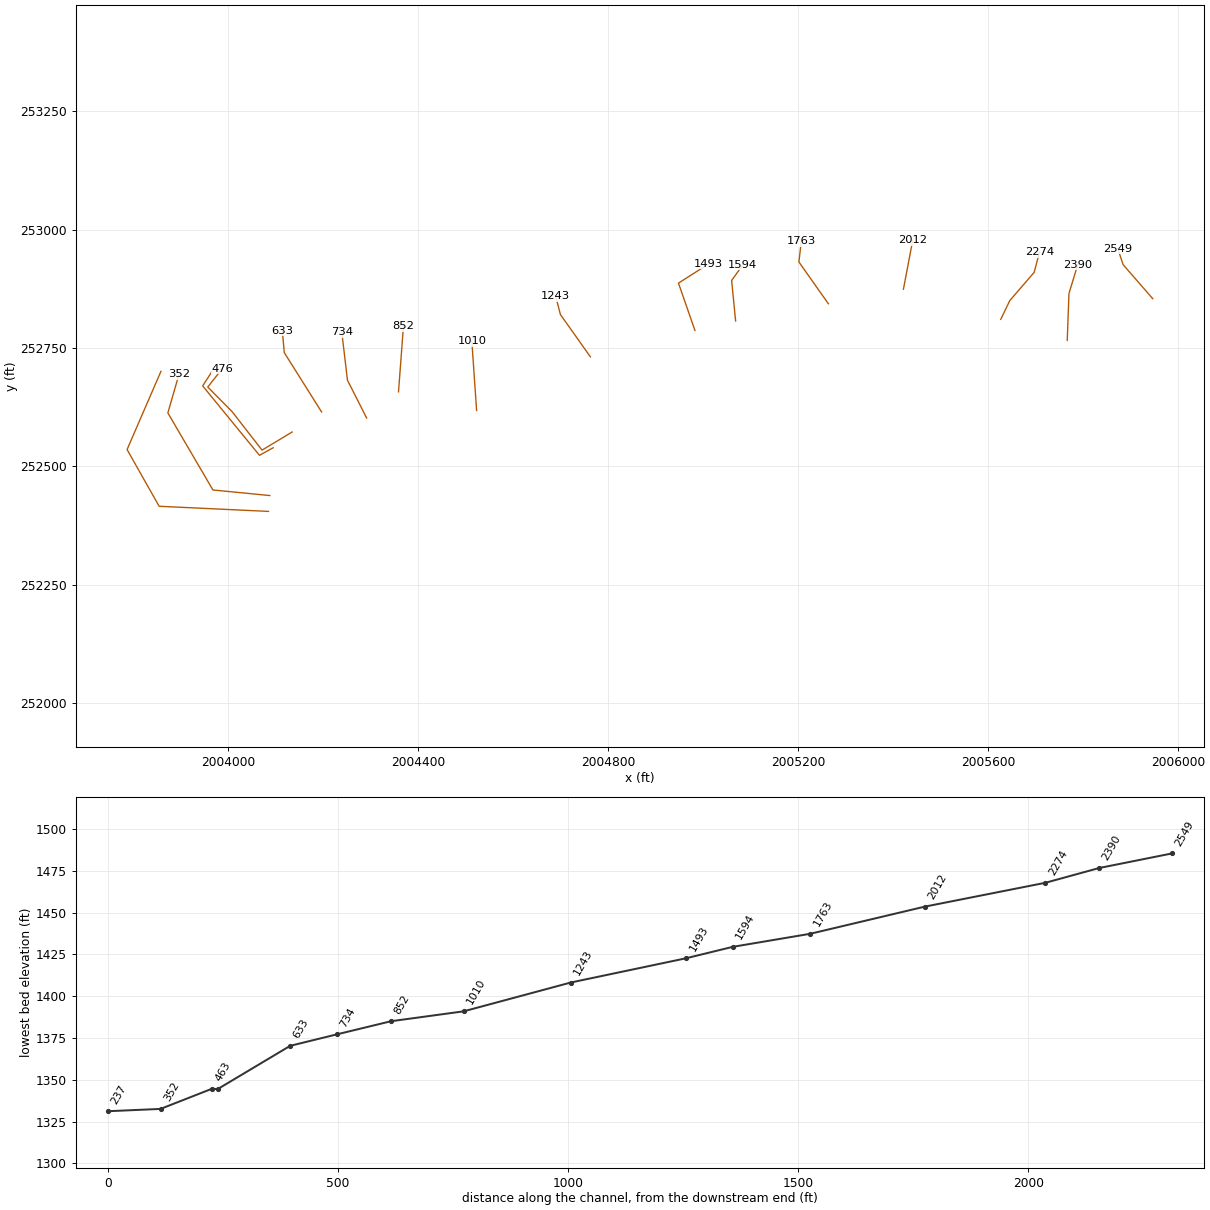
HEC-RAS study TUGCK.prj: TUGCK

--- TUGCK.g01 (geometry) --- (continued)

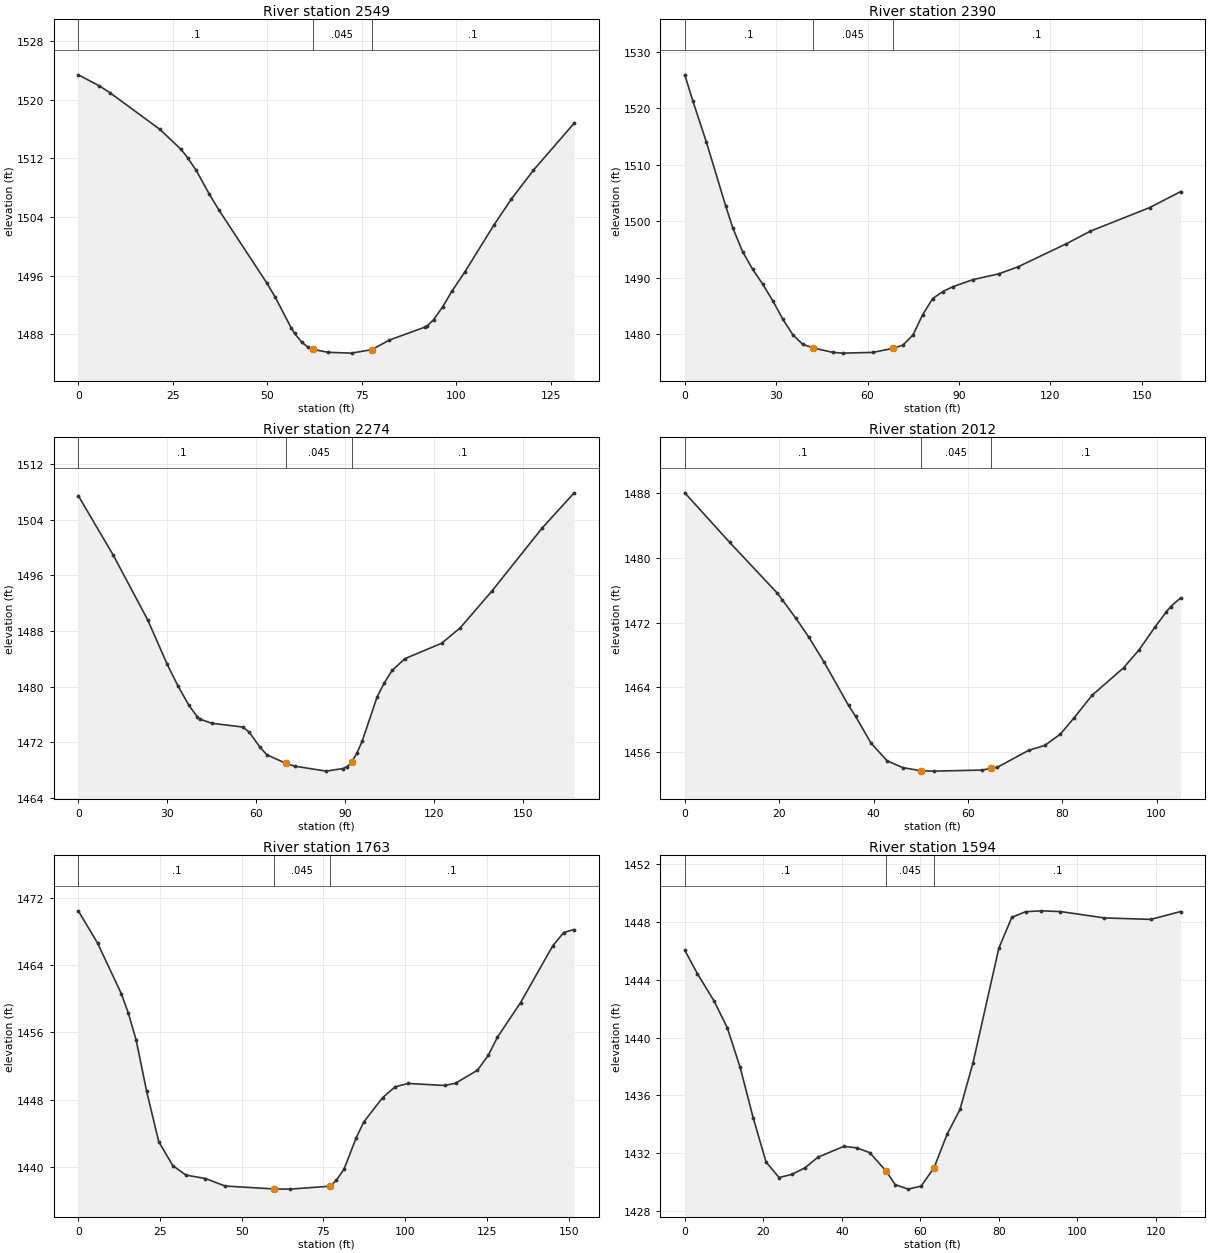
Type RM Length L Ch R = 1 ,2549    ,174.9,158.6,149
XS GIS Cut Line= 3
2005946.51838897252854.1768305322005883.98393586252926.203120275
2005872.81706924252960.262063487
#Sta/Elev= 30
       0  1523.4     5.6 1521.88     8.5 1520.91    21.6 1515.95    27.2 1513.21
    28.9  1512.1    31.2 1510.35    34.6 1507.17    37.2 1504.95    49.8 1495.05
    52.1 1493.06    56.3 1488.89    57.2 1488.13    59.1 1486.92    60.7 1486.26
      62 1485.94    66.1 1485.53    72.3 1485.42    77.7 1485.91    82.3  1487.2
    91.6 1488.95    92.3 1489.13      94 1489.98    96.4 1491.74    98.9 1493.91
   102.3 1496.52   109.9 1502.85   114.6 1506.46   120.4 1510.37   131.2  1516.8
#Mann= 3 ,-1 , 0
       0      .1       0      62    .045       0    77.7      .1       0
Bank Sta=62,77.7
XS Rating Curve= 0 ,0
Exp/Cntr(USF)=0,0
Exp/Cntr=0.3,0.1

Type RM Length L Ch R = 1 ,2390    ,130.6,116.5,106.9
XS GIS Cut Line= 3
2005766.46318143252766.1339095252005770.11814177252865.426998741
2005788.59599682252926.139951044
#Sta/Elev= 30
       0 1525.92     2.6 1521.37     7.1 1514.01    13.4 1502.77    15.8 1498.77
      19 1494.62    22.3  1491.5    25.6 1488.87    28.9 1485.94    32.2 1482.67
    35.5 1479.92    38.7 1478.25    42.1 1477.61    48.6 1476.81    51.9 1476.68
    61.7 1476.81    68.3 1477.52    71.6 1478.09    74.9 1479.88    78.1 1483.48
    81.4 1486.34    84.7 1487.57      88 1488.43    94.6 1489.68   103.1 1490.71
   109.5 1491.97   125.3 1496.04   133.2 1498.27   152.6 1502.42   162.8 1505.26
#Mann= 3 ,-1 , 0
       0      .1       0    42.1    .045       0    68.3      .1       0
Bank Sta=42.1,68.3
XS Rating Curve= 0 ,0
Exp/Cntr(USF)=0,0
Exp/Cntr=0.3,0.1

Type RM Length L Ch R = 1 ,2274    ,254.9,262.2,272
XS GIS Cut Line= 4
2005626.58766011252810.6260506872005645.57133338252850.268427212
2005696.93891986252910.0111636662005708.10578649 252953.00360018
#Sta/Elev= 30
       0 1507.43    11.8 1498.88    23.4 1489.59      30 1483.19    33.6 1480.11
    37.3 1477.32    40.1 1475.69    40.9 1475.35      45 1474.75    55.5  1474.2
    57.6 1473.49    61.3 1471.28    63.6 1470.21      701468.987    72.9 1468.59
    83.6 1467.87    89.2 1468.24    90.7 1468.53    92.2 1469.17    93.9 1470.43
    95.7 1472.15   100.8 1478.59   103.2 1480.55   105.8 1482.33   110.1 1484.02
   122.5 1486.24   128.8 1488.46   139.5 1493.76   156.5 1502.84   167.2 1507.85
#Mann= 3 ,-1 , 0
       0      .1       0      70    .045       0    92.2      .1       0
Bank Sta=70,92.2
XS Rating Curve= 0 ,0
Exp/Cntr(USF)=0,0
Exp/Cntr=0.3,0.1

Type RM Length L Ch R = 1 ,2012    ,236.4,249,257.6
XS GIS Cut Line= 2
2005421.67565751 252874.277190462005441.21767411252977.570706759
#Sta/Elev= 28
       0 1488.07     9.5 1481.94    19.5 1475.71    20.7 1474.79    23.5 1472.56
    26.3 1470.18    29.5 1467.12    34.7 1461.74    36.2 1460.38    39.5 1457.04
    42.9 1454.86    46.2 1454.03      501453.634    52.9 1453.59    62.9 1453.72
      65 1453.93    66.2 1454.05    72.9 1456.17    76.3 1456.77    79.6 1458.17
    82.5 1460.18    86.3 1462.97      93 1466.39    96.3 1468.62    99.6 1471.39
   102.1 1473.35     103 1473.98   105.1 1475.06
#Mann= 3 ,-1 , 0
       0      .1       0      50    .045       0      65      .1       0
Bank Sta=50,65
XS Rating Curve= 0 ,0
Exp/Cntr(USF)=0,0
Exp/Cntr=0.3,0.1

Type RM Length L Ch R = 1 ,1763    ,175.4,168.3,161.9
XS GIS Cut Line= 3
2005263.66449474252843.5683072362005201.68838496252931.786553589
2005206.71347494252975.337333434
#Sta/Elev= 30
       0 1470.43     5.9 1466.58    13.2 1460.54    15.3 1458.27    17.7 1455.05
    20.9 1448.97    24.6 1442.99    28.9 1440.15    32.9 1439.02    38.9 1438.61
    44.9 1437.72      601437.368    64.8 1437.35      77  1437.7    78.9 1438.38
    81.3 1439.74      85 1443.44    87.3 1445.32    93.1 1448.23      97 1449.53
     101 1449.91   112.1 1449.67   115.4 1449.94   122.1 1451.48   125.4 1453.24
   128.2 1455.39   135.3 1459.52   145.2  1466.3   148.5 1467.85   151.7 1468.21
#Mann= 3 ,-1 , 0
       0      .1       0      60    .045       0      77      .1       0
Bank Sta=60,77
XS Rating Curve= 0 ,0
Exp/Cntr(USF)=0,0
Exp/Cntr=0.3,0.1

Type RM Length L Ch R = 1 ,1594    ,99.1,101.6,104.3
XS GIS Cut Line= 3
2005068.46467957252807.239646305 2005060.0895296252892.666176001
2005083.53994952 252925.60843255
#Sta/Elev= 30
       0 1446.02     3.2 1444.41     7.5  1442.5    10.8 1440.69    14.1 1437.94
    17.4 1434.48    20.7 1431.41      24 1430.34    27.3 1430.56    30.6 1431.01
    33.9 1431.74    40.5 1432.49    43.8 1432.39    47.1 1432.06    51.3 1430.78
    53.6 1429.85    56.9 1429.54    60.2 1429.75    63.5 1431.02    66.8 1433.32
    70.1 1435.04    73.4 1438.24      80 1446.17    83.3 1448.29    86.8 1448.68
    90.8 1448.74    95.7 1448.69   106.9 1448.25   118.7 1448.15   126.3 1448.69
#Mann= 3 ,-1 , 0
       0      .1       0    51.3    .045       0    63.5      .1       0
Bank Sta=51.3,63.5
XS Rating Curve= 0 ,0
Exp/Cntr(USF)=0,0
Exp/Cntr=0.3,0.1

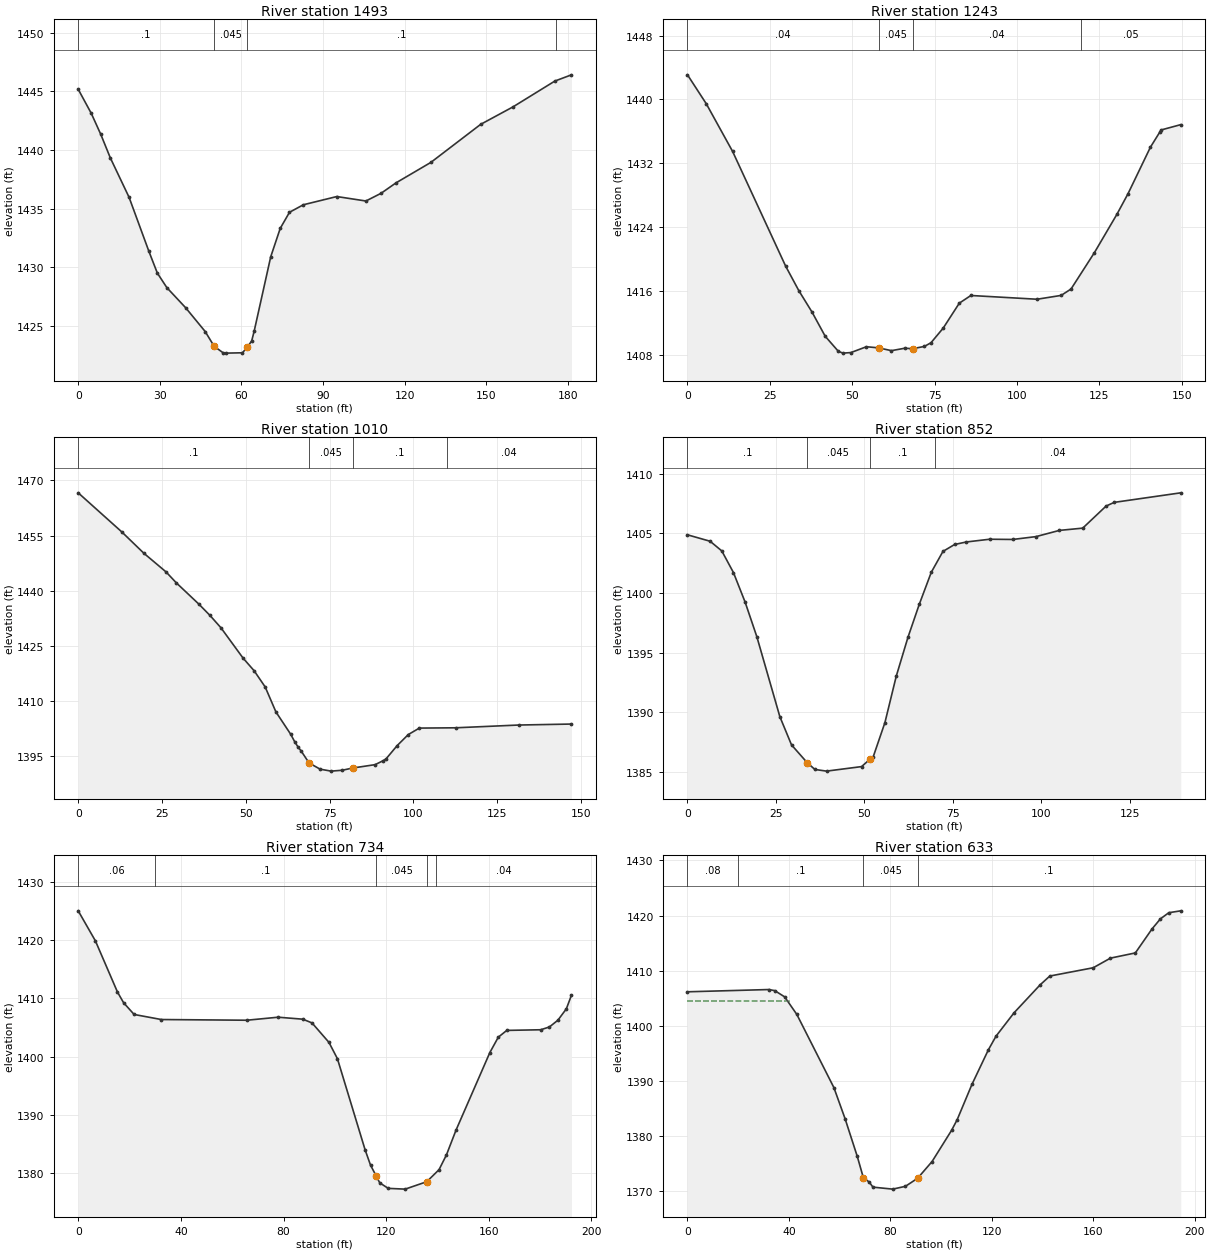
Type RM Length L Ch R = 1 ,1493    ,246,250,251.8
XS GIS Cut Line= 3
2004982.81779907 252787.175630772004948.20051253252887.119087081
 2005011.8516523252927.878150269
#Sta/Elev= 30
       0 1445.18     4.8 1443.13     8.3 1441.34    11.8 1439.34    18.7 1435.98
      26 1431.37    29.1 1429.52    32.6 1428.28    39.5 1426.57    46.7 1424.54
      50 1423.28    53.4 1422.71    54.4  1422.7    60.4 1422.73    62.1 1423.18
    63.8 1423.74    64.7 1424.56    70.8 1430.91    74.3 1433.33    77.7  1434.7
    82.8 1435.34    95.1 1436.04   105.8 1435.66   111.4 1436.32   116.9 1437.21
   129.7 1438.95     148 1442.19   159.9 1443.68   175.3 1445.88   181.4 1446.41
#Mann= 4 ,-1 , 0
       0      .1       0      50    .045       0    62.1      .1       0
  175.77     .05       0
Bank Sta=50,62.1
XS Rating Curve= 0 ,0
Exp/Cntr(USF)=0,0
Exp/Cntr=0.3,0.1

Type RM Length L Ch R = 1 ,1243    ,239.6,232.9,228
XS GIS Cut Line= 3
2004762.83052652252731.3412976362004699.73773008252820.676230651
2004689.68755012252859.760263845
#Sta/Elev= 30
       0 1443.08     5.7 1439.46    13.7 1433.48    29.8 1419.11    33.8 1416.04
    37.8 1413.36    41.8 1410.33    45.8 1408.44    47.2 1408.22    49.6 1408.29
    54.3 1409.02      581408.881    61.9 1408.53    65.9 1408.83    68.4 1408.78
    71.9 1409.06    73.9 1409.52    77.6 1411.35    82.5 1414.48      86 1415.44
   106.1 1414.97   113.4 1415.45   116.4 1416.25   123.5 1420.81   130.3 1425.59
   133.7 1428.19   140.5 1434.02   143.3 1435.88   143.8 1436.18   149.7 1436.84
#Mann= 4 ,-1 , 0
       0     .04       0      58    .045       0    68.4     .04       0
  119.37     .05       0
Bank Sta=58,68.4
XS Rating Curve= 0 ,0
Exp/Cntr(USF)=0,0
Exp/Cntr=0.3,0.1

Type RM Length L Ch R = 1 ,1010    ,159.4,157.7,156.2
XS GIS Cut Line= 2
2004523.30123738252617.9976013732004513.25105741252764.841897517
#Sta/Elev= 30
       0 1466.64      13 1456.02    19.6 1450.21    26.2 1445.15    29.3 1442.15
      36 1436.39    39.3 1433.33    42.6 1429.95    49.2  1421.7    52.5 1418.27
    55.8 1413.86      59 1407.08    63.4 1401.02    64.6 1398.98    65.6 1397.54
    66.5 1396.49    68.9  1393.2    72.2 1391.51    75.5 1390.98    78.8 1391.22
    81.9 1391.82    88.6 1392.74    91.1 1393.86    91.9 1394.35    95.2 1397.94
    98.5 1400.92   101.8 1402.68   112.6 1402.76   131.4 1403.51   147.2 1403.78
#Mann= 4 ,-1 , 0
       0      .1       0    68.9    .045       0    81.9      .1       0
     110     .04       0
Bank Sta=68.9,81.9
XS Rating Curve= 0 ,0
Exp/Cntr(USF)=0,0
Exp/Cntr=0.3,0.1

Type RM Length L Ch R = 1 ,852     ,114.3,118.1,120.2
XS GIS Cut Line= 2
2004358.94827434252657.3963639912004369.34942702252796.393586142
#Sta/Elev= 30
       0 1404.88     6.4 1404.34     9.7 1403.53      13 1401.71    16.3 1399.23
    19.6 1396.34    26.1 1389.64    29.4 1387.27    33.8 1385.79      36 1385.21
    39.3 1385.07    49.2 1385.45    51.5 1386.05    52.5 1386.28    55.8 1389.14
      59 1393.03    62.3 1396.28    65.5 1399.05    68.9 1401.74    72.2 1403.49
    75.5 1404.07    78.8 1404.28    85.4 1404.51    91.9 1404.49    98.5 1404.73
   105.1 1405.25   111.7 1405.44   118.3 1407.29   120.6  1407.6   139.4  1408.4
#Mann= 4 ,-1 , 0
       0      .1       0    33.8    .045       0    51.5      .1       0
      70     .04       0
Bank Sta=33.8,51.5
XS Rating Curve= 0 ,0
Exp/Cntr(USF)=0,0
Exp/Cntr=0.3,0.1

Type RM Length L Ch R = 1 ,734     ,93.1,100.8,106.5
XS GIS Cut Line= 3
2004291.87372127252602.0416871372004251.48588031252681.981758572
2004239.50879643252783.926239914
#Sta/Elev= 30
       0 1425.08     6.7 1419.91    15.3  1411.1    17.7 1409.25    21.8 1407.24
    32.4 1406.37    65.7 1406.25    77.9 1406.77    87.5 1406.43    91.1 1405.79
    97.7 1402.44     101 1399.63   111.8 1383.93   113.9 1381.31   116.21379.361
   117.5 1378.26   120.8 1377.31   127.4 1377.18   135.81378.455   140.6 1380.53
   143.5 1383.09   147.2 1387.32   160.4 1400.69   163.7 1403.34     167  1404.5
   180.2 1404.61   183.6 1405.09   186.9 1406.25   190.2 1408.21   192.2 1410.56
#Mann= 5 ,-1 , 0
       0     .06       0      30      .1       0   116.2    .045       0
   135.8      .1       0  139.56     .04       0
Bank Sta=116.2,135.8
XS Rating Curve= 0 ,0
Exp/Cntr(USF)=0,0
Exp/Cntr=0.5,0.3

Type RM Length L Ch R = 1 ,633     ,156.1,157.5,158.6
XS GIS Cut Line= 3
 2004197.0539062 252614.925092312004118.46149889252740.301087363
 2004114.4414269252786.531915198
#Sta/Elev= 30
       0 1406.17    32.1 1406.58    34.4 1406.38    38.3 1405.25    43.1 1402.06
    57.7 1388.79    62.1 1383.16    66.9 1376.33    69.3 1372.46    71.6 1371.66
    73.1 1370.73    80.9 1370.37    85.9 1370.88    90.7 1372.34    96.4 1375.38
   104.1 1381.05   106.3 1382.98   112.1 1389.36   118.6 1395.66   121.6 1398.12
   128.7 1402.36     139 1407.44   142.8 1409.03   159.9 1410.53   166.7 1412.28
   176.5 1413.22   183.1 1417.59   186.4 1419.41   189.7 1420.52   194.4 1420.86
#Mann= 4 ,-1 , 0
       0     .08       0      20      .1       0    69.3    .045       0
    90.7      .1       0
#XS Ineff= 2 , 0
              40  1404.5     140          1404.5
Permanent Ineff=
       F       F
Bank Sta=69.3,90.7
XS Rating Curve= 0 ,0
Exp/Cntr(USF)=0,0
Exp/Cntr=0.5,0.3

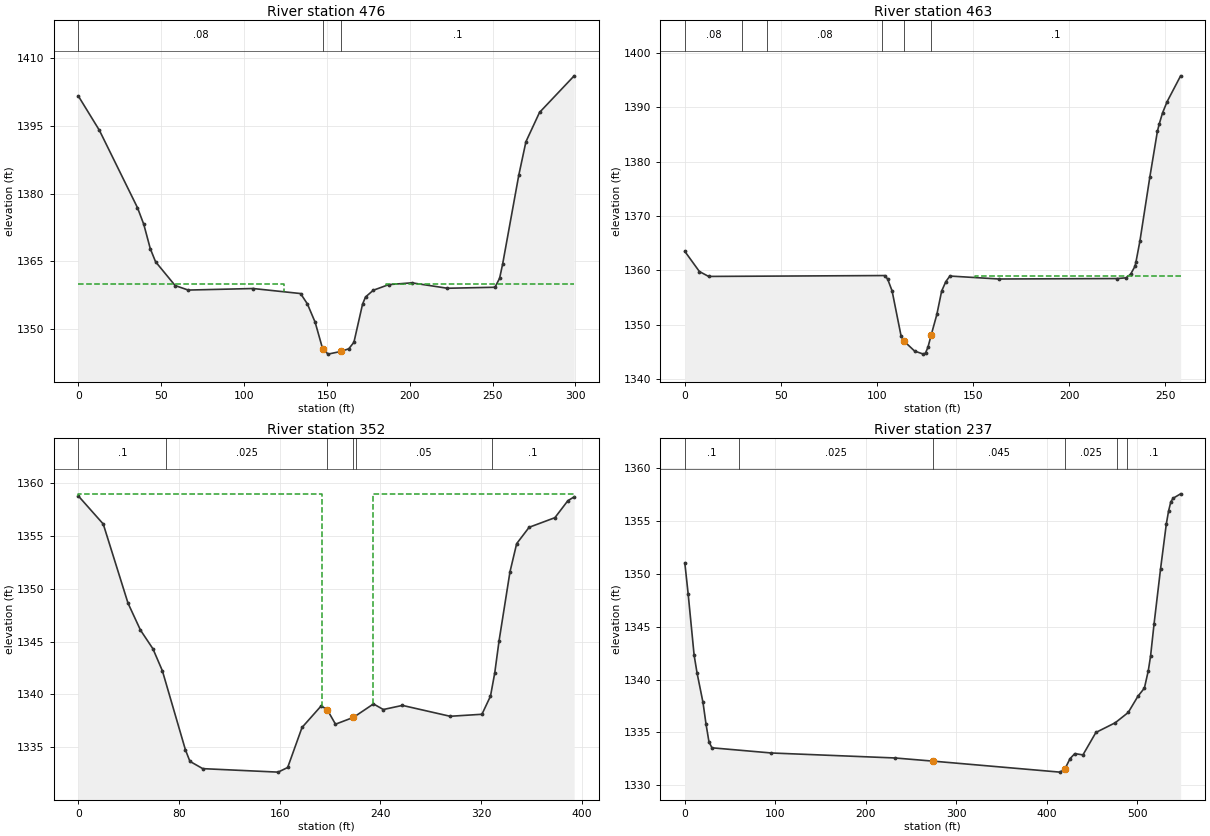
Type RM Length L Ch R = 1 ,476     ,13.1,13.1,14.5
XS GIS Cut Line= 5
2004135.11000721252572.5568755912004071.68145894252534.324003352
2004008.33643279252615.9712317012003957.51467133252667.587922129
2003987.92635173252706.411343907
#Sta/Elev= 30
       0 1401.55    12.7 1393.97    35.7 1376.86    39.5 1373.18    43.4 1367.83
    46.6 1364.92    58.4 1359.66    66.3 1358.66   105.5    1359   134.1 1357.89
   138.2 1355.61   142.9 1351.55   147.41345.706   150.7  1344.5   158.41345.094
   163.2 1345.68   166.3 1347.12   171.5 1355.53   173.3 1357.13     178 1358.62
   187.3 1359.86   201.2 1360.26   222.7 1359.06   251.4 1359.28   254.2 1361.25
     256 1364.33   265.8 1384.08   270.1 1391.45   278.3 1397.92   299.2 1406.01
#Mann= 3 ,-1 , 0
       0     .08       0   147.4    .045       0   158.4      .1       0
#XS Ineff= 2 , 0
           124.2    1360   185.8            1360
Permanent Ineff=
       F       F
Bank Sta=147.4,158.4
XS Rating Curve= 0 ,0
Exp/Cntr(USF)=0,0
Exp/Cntr=0.5,0.3

Type RM Length L Ch R = 1 ,463     ,113.1,111.1,108.4
XS GIS Cut Line= 4
2004094.98838197252539.2910525232004066.33232906252523.243662895
2003946.74106826 252669.962653782003966.22718424252700.147029509
#Sta/Elev= 30
       0 1363.51     7.6  1359.8    12.4  1358.9   104.1 1359.06   105.6  1358.4
   107.9 1356.25   112.6 1347.94   114.21346.987   119.6  1345.2   124.2 1344.63
   125.3 1344.84   126.6 1345.92   128.2 1348.07   131.2 1351.91   133.7 1356.21
   135.9 1357.96     138 1358.97   163.4 1358.43     225 1358.51   229.7 1358.64
   232.1 1359.32   234.3 1360.74   234.8 1361.46   236.9 1365.38   242.1 1377.21
     246 1385.52   246.9 1386.82   248.7 1388.94   251.1 1391.02   258.1 1395.74
#Mann= 6 ,-1 , 0
       0     .08       0      30      .1       0   42.84     .08       0
  102.84      .1       0   114.2    .045       0   128.2      .1       0
#XS Ineff= 2 , 0
              95    1359     151            1359
Permanent Ineff=
       F       F
Bank Sta=114.2,128.2
XS Rating Curve= 0 ,0
Exp/Cntr(USF)=0,0
Exp/Cntr=0.5,0.3

Type RM Length L Ch R = 1 ,352     ,114.7,114.7,114.7
XS GIS Cut Line= 4
2004088.10169415252438.311675493 2003968.2887322252450.104289859
2003873.44832396252612.9442162412003897.06134143252694.918964088
#Sta/Elev= 30
       0  1358.8    19.8 1356.14    39.5 1348.64    49.4 1346.09    59.3 1344.32
    66.8 1342.24    85.1 1334.76    88.7 1333.66    98.9 1332.97   158.8 1332.64
   166.4 1333.08   177.8 1336.87     193 1338.91   197.81338.561   204.4 1337.18
   218.71337.828   234.6  1339.1   242.4 1338.57   257.6 1338.96   295.5 1337.93
   320.8 1338.12   327.6 1339.84     331 1342.05   334.4 1345.07   343.1 1351.62
   348.4 1354.28   358.3 1355.83   378.8 1356.74   389.1 1358.35   394.1 1358.71
#Mann= 6 ,-1 , 0
       0      .1       0      70    .025       0   197.8    .045       0
   218.7    .025       0  220.39     .05       0  328.84      .1       0
#XS Ineff= 2 , 0
             194    1359     234            1359
Permanent Ineff=
       F       F
Bank Sta=197.8,218.7
XS Rating Curve= 0 ,0
Exp/Cntr(USF)=0,0
Exp/Cntr=0.5,0.3

Type RM Length L Ch R = 1 ,237     ,,,
XS GIS Cut Line= 4
2004085.27146671252404.8206506952003855.07963429252415.669855912
2003787.62588012252535.4828178662003858.85327089252700.579418983
#Sta/Elev= 30
       0 1351.05     3.7 1348.12    10.3 1342.31    13.6  1340.6    20.1 1337.84
    23.4 1335.82    26.7 1334.11      30 1333.55    95.7 1333.06   231.9 1332.59
   274.2 1332.29   414.3 1331.25   419.6  1331.5   425.5 1332.52   430.8    1333
   439.8 1332.88   454.1    1335   475.5 1335.92   489.8 1336.89   500.5 1338.42
   507.7  1339.2     512 1340.85   514.5 1342.22   518.4  1345.3   525.5 1350.45
   531.9 1354.72   534.4 1355.95   536.9 1356.82   539.4 1357.15   547.7 1357.57
#Mann= 6 ,-1 , 0
       0      .1       0      60    .025       0   274.2    .045       0
   419.6    .025       0  477.94     .05       0  487.94      .1       0
Bank Sta=274.2,419.6
XS Rating Curve= 0 ,0
Exp/Cntr(USF)=0,0
Exp/Cntr=0.3,0.1
LCMann Table=0

Chan Stop Cuts=-1
Use User Specified Reach Order=0
Composite Channel Slope=5